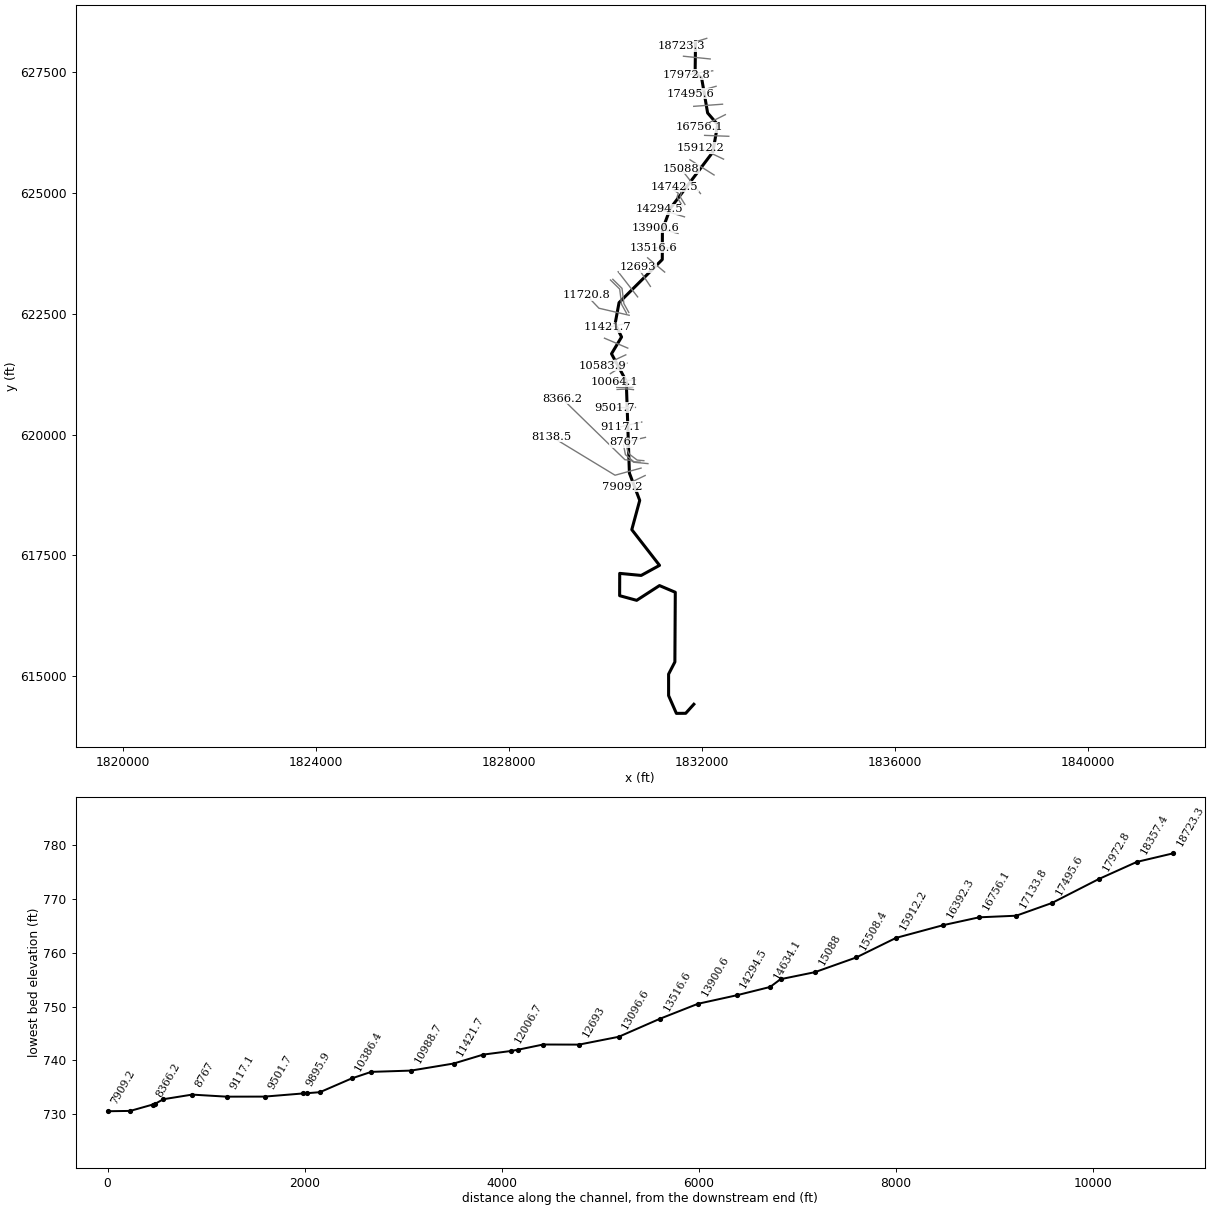
--- CoxFork.prj (project) ---

Proj Title=CoxFork
Current Plan=p01
Default Exp/Contr=0,0
English Units
Geom File=g01
Flow File=f01
Plan File=p01
BEGIN DESCRIPTION:
AMEC Environment & Infrastructure, 2013
Projection: NAD 1983 State Plane West Virginia South FIPS 4702 (US Feet)
Vertical Datum: NAVD 1988
END DESCRIPTION:
DSS Export Rating Curves= 0
DSS Export Rating Curve Sorted= 0
DSS Export Volume Flow Curves= 0
DXF OffsetX= 0
DXF OffsetY= 0
DXF ScaleX= 0
DXF ScaleY= 0

--- CoxFork.p01 (plan) ---

Plan Title=Floodplain
Program Version=4.00
Geom File=g01
Flow File=f01
K Sum by GR=0
Std Step Tol=0.01
Critical Tol=0.01
Num of Std Step Trials=20
Max Error Tol=0.3
Flow Tol Ratio=0.001
Split Flow NTrial=30
Split Flow Tol=0.02
Split Flow Ratio=0.02
Log Output Level=0
Friction Slope Method=1
Unsteady Friction Slope Method=2
Unsteady Bridges Friction Slope Method=1
Global Log Level=0
CheckData=False
Run HTab=0
Run UNet=0
Run PostProcess=0
UNET Theta=0
UNET Theta Warmup=0
UNET ZTol=0
UNET ZSATol=0
UNET MxIter=0
UNET MaxInSteps=0
UNET DtIC=0
UNET DtMin=0
UNET MaxCRTS=0
UNET WFStab=0
UNET SFStab=0
UNET WFX=0
UNET SFX=0
UNET DSS MLevel=0
UNET DZMax Abort=0
UNET Convert EG Bridges=0
UNET Use Existing IB Tables=0
UNET Froude Limit=0
UNET Froude Power=0
Write IC File=0
Echo Input=False
Echo Output=False
Write Detailed=0

--- CoxFork.f01 (steady flow) ---

Flow Title=NFF Regression Equation
Program Version=4.00
Number of Profiles=1
Profile Names=P100yr
River Rch & RM=CoxFork,Main      ,18723.3
815.3250
River Rch & RM=CoxFork,Main      ,18357.4
930.1523
River Rch & RM=CoxFork,Main      ,16392.3
1024.549
River Rch & RM=CoxFork,Main      ,15508.4
1074.293
River Rch & RM=CoxFork,Main      ,11720.8
1183.672
River Rch & RM=CoxFork,Main      ,11421.7
1469.995
River Rch & RM=CoxFork,Main      ,7909.2
1573.891
River Rch & RM=CoxFork,Main      ,7496.3
2045.573
River Rch & RM=CoxFork,Main      ,592.8
2183.424
River Rch & RM=CoxFork,Main      ,140.7
2183.424
Boundary for River Rch & Prof#=CoxFork,Main      ,1
Up Type=0
Dn Type=3
Dn Slope=0.002832

--- CoxFork.g01 (geometry) ---

Geom Title=USGS 3m DEM
Program Version=4.10

River Reach=CoxFork         ,Main
Reach XY= 30
     1831872.771      628132.437     1831864.128      627482.905
     1831997.861       627389.13     1832122.949      626659.718
     1832331.369      626418.079     1832230.674      625848.678
     1831350.231      624683.289     1831186.169      624241.076
     1831183.571      623623.884     1830287.482       622731.16
     1830205.883      622293.504     1830339.359      622019.669
     1830131.242      621671.757     1830436.937      621105.607
     1830502.107      619201.098     1830716.046      618635.248
     1830551.743      618029.902     1831126.637      617290.098
     1830746.311      617081.671     1830301.208       617123.92
     1830299.706      616662.365     1830652.558      616565.864
     1831125.504      616871.552     1831453.171      616732.634
     1831444.571       615289.43     1831314.333        615037.6
     1831314.358      614593.003     1831475.893      614224.831
     1831668.667      614226.579     1831837.589      614413.647

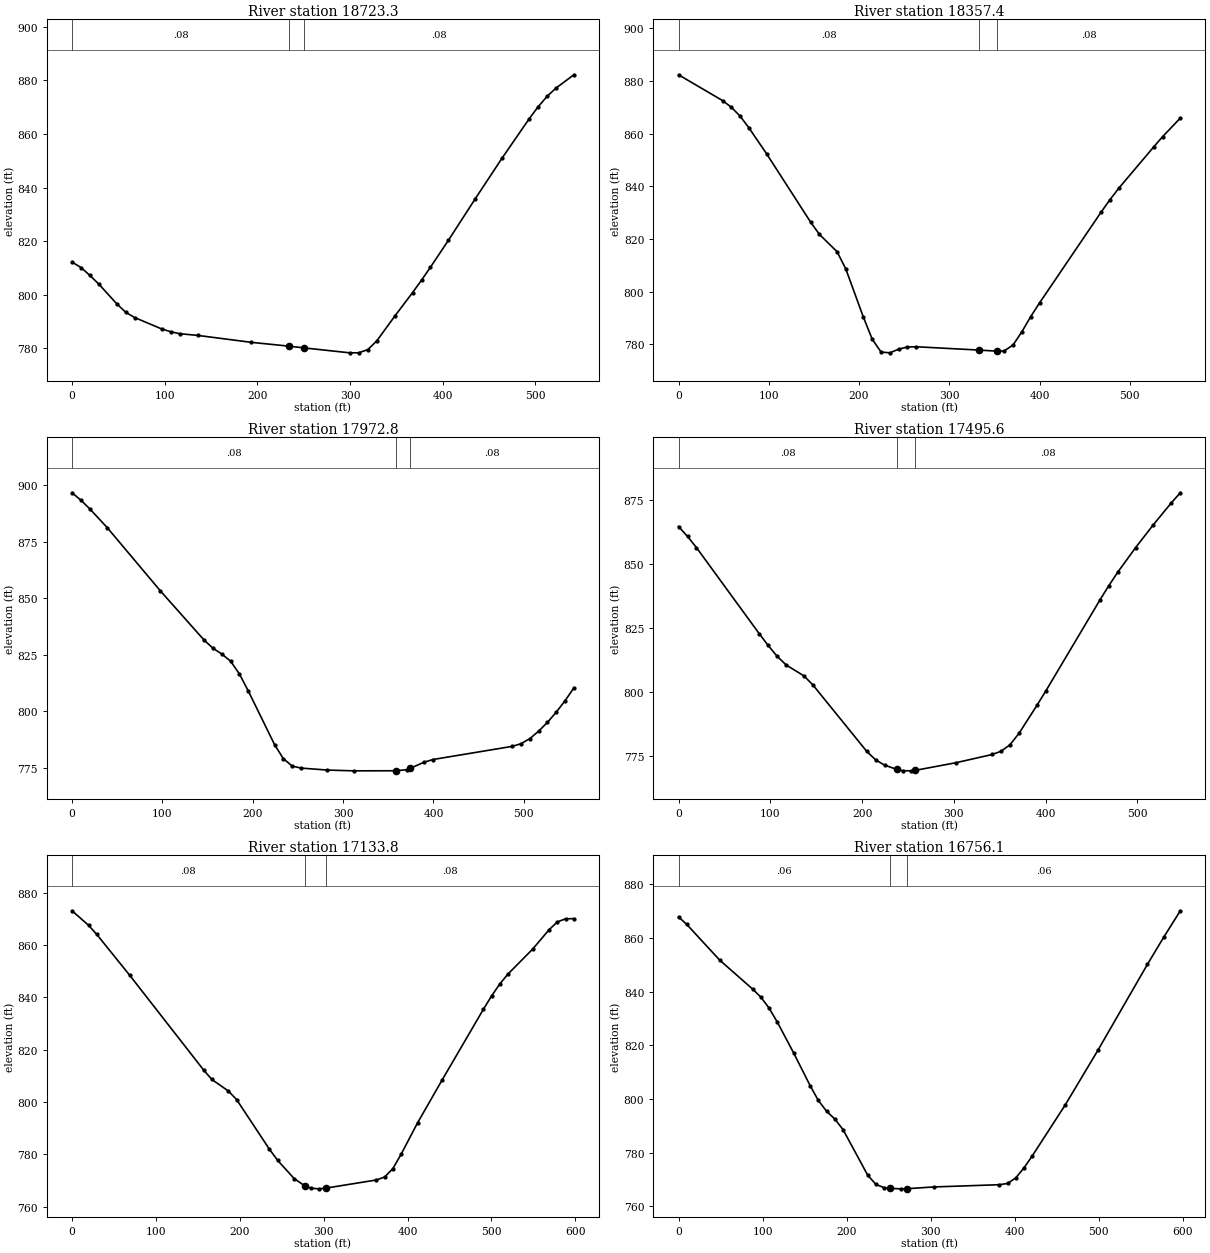
Type RM Length L Ch R = 1 ,18723.3 ,374.2,365.9,357.7
XS GIS Cut Line= 2
     1832104.985      628204.733     1831588.004      628043.318
#Sta/Elev= 30
       0   812.2     9.7  810.16    19.3  807.21      29  803.95    48.4  796.58
      58  793.47    67.7   791.5    96.7  787.28   106.4  786.24   116.1   785.5
   135.4  784.87   193.4  782.28   234.4780.8405   250.8780.1857   299.8  778.36
   309.5  778.38   319.2  779.57   328.8  782.78   348.2     792   367.5  800.83
   377.2  805.47   386.8  810.29   406.2  820.33   435.2  835.84   464.2  851.02
   493.2  865.56   502.9  870.07   512.6  873.97   522.2  877.07   541.6  882.06
#Mann= 3 , 0 , 0
       0     .08       0   234.4    .045       0   250.8     .08       0
Bank Sta=234.4,250.8
XS Rating Curve= 0 ,0
Exp/Cntr=0.3,0.1

Type RM Length L Ch R = 1 ,18357.4 ,426.8,384.3,388.2
XS GIS Cut Line= 2
     1832176.084       627777.56     1831622.956      627834.272
#Sta/Elev= 30
       0   882.4    48.8  872.59    58.5  870.09    68.3  866.65      78  862.24
    97.6  852.38   146.3  826.46   156.1  821.78   175.6  815.22   185.3  808.68
   204.8  790.36   214.6  781.96   224.4  777.09   234.1  776.78   243.9  778.18
   253.6     779   263.4  779.09   333.2777.8274   353.4777.4028   360.9  777.52
   370.7  779.78   380.4  784.77   390.2  790.53     400  795.74   468.2  830.22
     478  834.94   487.7  839.26   526.8  855.12   536.5  858.94     556  865.95
#Mann= 3 , 0 , 0
       0     .08       0   333.2    .045       0   353.4     .08       0
Bank Sta=333.2,353.4
XS Rating Curve= 0 ,0
Exp/Cntr=0.3,0.1

Type RM Length L Ch R = 1 ,17972.8 ,429.5,477.2,477.3
XS GIS Cut Line= 2
      1832228.56      627532.807     1831679.566      627448.813
#Sta/Elev= 30
       0  896.54     9.7  893.28    19.5  889.48      39  881.09    97.4  853.33
   146.2  831.39   155.9  827.85   165.6  825.29   175.4  822.12   185.1  816.54
   194.9  809.04   224.1  785.23   233.8  779.02   243.6  775.75   253.3  774.84
   282.6  773.96   311.8  773.62   358.5773.6585   370.3  774.14   374.1774.7101
   389.7  777.44   399.5  778.63   487.2  784.44   496.9  785.62   506.7  787.87
   516.4  791.16   526.2  795.06   535.9  799.56   545.6  804.58   555.4  810.29
#Mann= 3 , 0 , 0
       0     .08       0   358.5    .045       0   374.1     .08       0
Bank Sta=358.5,374.1
XS Rating Curve= 0 ,0
Exp/Cntr=0.3,0.1

Type RM Length L Ch R = 1 ,17495.6 ,363.3,361.3,365.6
XS GIS Cut Line= 2
     1832298.553      627211.893     1831773.027       627061.21
#Sta/Elev= 30
       0  864.69     9.8   860.8    19.5  856.47    87.9   822.8    97.6  818.21
   107.4  813.96   117.2  810.58   136.7  806.27   146.4  802.75     205   776.8
   214.8  773.45   224.5   771.4   237.8769.7365   244.1  769.22   253.8  769.17
   258.1769.3736   302.6  772.37   341.7  775.56   351.4  776.83   361.2  779.39
     371  783.86   390.5  794.78   400.3  800.49   458.8  835.79   468.6  841.46
   478.4  846.77   497.9  856.41   517.4  865.43   536.9  873.95   546.7  877.88
#Mann= 3 , 0 , 0
       0     .08       0   237.8    .045       0   258.1     .08       0
Bank Sta=237.8,258.1
XS Rating Curve= 0 ,0
Exp/Cntr=0.3,0.1

Type RM Length L Ch R = 1 ,17133.8 ,368.9,377.2,380.2
XS GIS Cut Line= 2
     1832431.884      626840.698     1831835.229      626796.445
#Sta/Elev= 30
       0  873.12    19.6  867.59    29.4   864.1    68.7  848.47   156.9  812.22
   166.7  808.62   186.4  804.21   196.2  800.95   235.4  781.91   245.2  777.68
   264.8  770.74   277.3767.9902   284.4  767.08     294  766.82   302.3767.0773
   362.9  770.21   372.7  771.35   382.5  774.56   392.3  780.02   411.9  792.03
   441.4  808.53   490.4  835.44   500.2  840.57     510  845.14   519.8  848.96
   549.2  858.47   568.9  865.94   578.7  868.88   588.5  870.06   598.3  870.11
#Mann= 3 , 0 , 0
       0     .08       0   277.3    .045       0   302.3     .08       0
Bank Sta=277.3,302.3
XS Rating Curve= 0 ,0
Exp/Cntr=0.3,0.1

Type RM Length L Ch R = 1 ,16756.1 ,373.5,363.4,367
XS GIS Cut Line= 2
     1832490.515      626624.161     1831955.727      626358.339
#Sta/Elev= 30
       0  867.78     9.8  864.98      49  851.68    88.1  840.93    97.9  837.92
   107.7  833.84   117.5  828.65   137.1  817.06   156.6  804.97   166.4  799.42
   176.2  795.42     186  792.51   195.8  788.56   225.2  771.57     235  768.15
   244.8  766.94   251.7766.7147   264.3  766.52   271.4  766.56   303.5  767.22
   381.8  768.06   391.6  768.52   401.4  770.62   411.2  774.36     421  778.79
   460.2  797.75   499.3  818.22     558  850.09   577.6   860.3   597.2  870.06
#Mann= 3 , 0 , 0
       0     .06       0   251.7    .045       0   271.4     .06       0
Bank Sta=251.7,271.4
XS Rating Curve= 0 ,0
Exp/Cntr=0.3,0.1

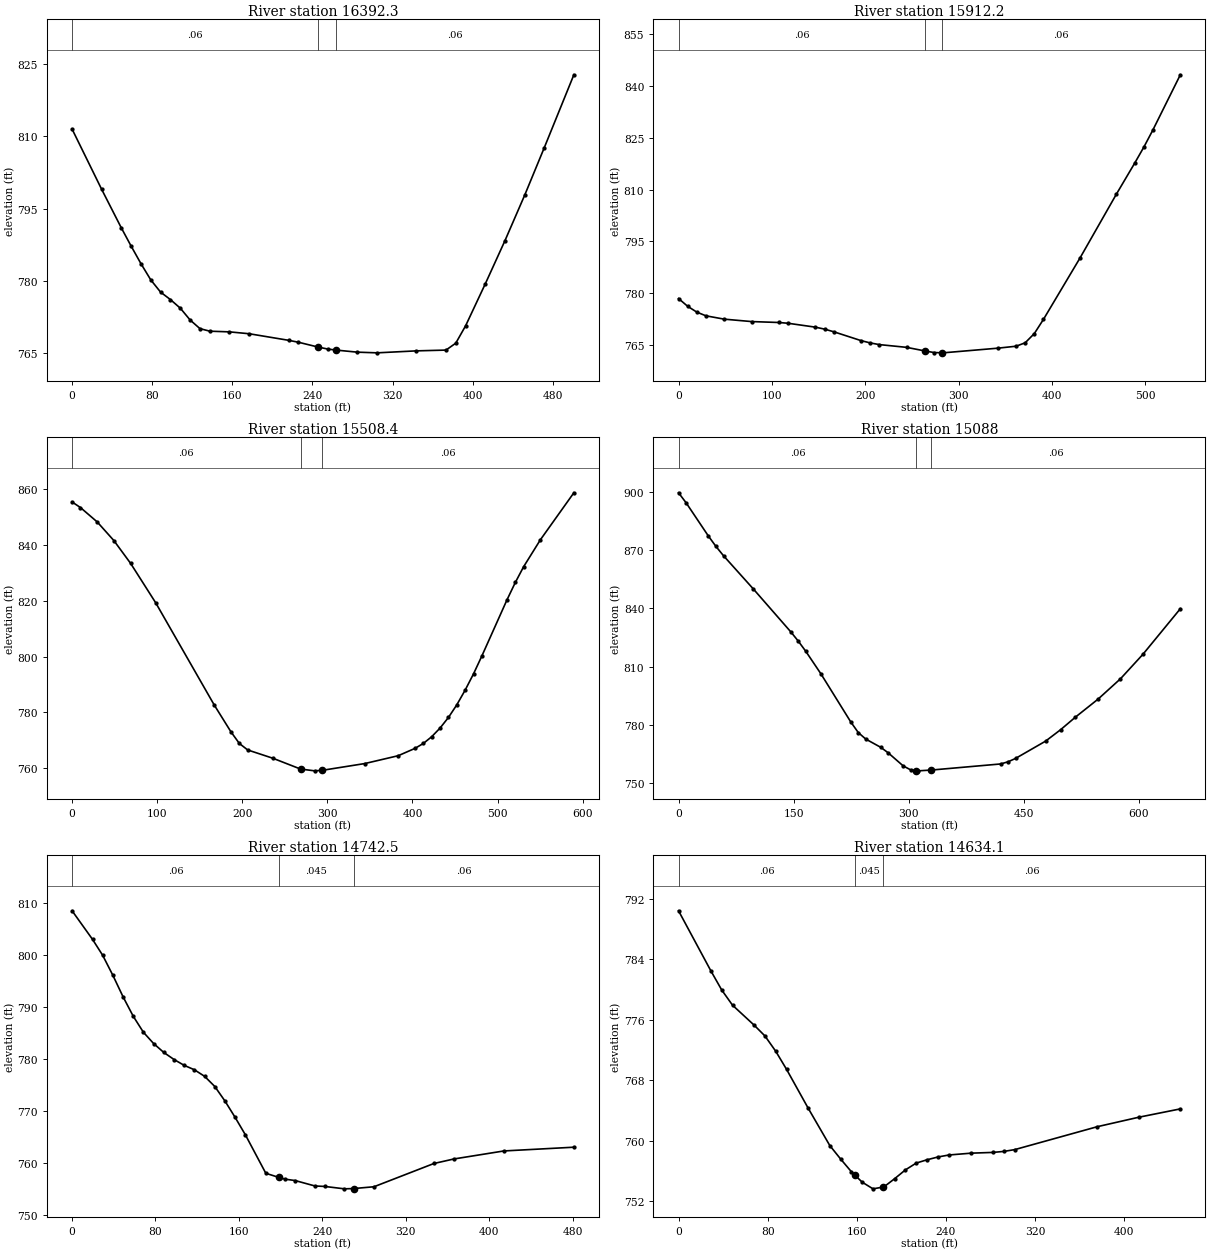
Type RM Length L Ch R = 1 ,16392.3 ,486.6,479,454.8
XS GIS Cut Line= 2
     1832561.705      626176.127     1832060.977      626195.194
#Sta/Elev= 30
       0  811.48    29.5     799    49.1  791.02      59   787.2    68.8  783.56
    78.6   780.2    88.4  777.66    98.2  776.12   108.1  774.33   117.9  771.88
   127.7  770.09   137.6  769.56   157.2  769.42   176.9  769.03   216.2  767.67
     226  767.27   245.9766.2574   255.5  765.85   263.5 765.645   284.9  765.21
   304.6  765.07   343.9  765.48   373.4  765.64   383.2  767.08     393  770.68
   412.7   779.4   432.3  788.34     452  797.77   471.6  807.64   501.1  822.74
#Mann= 3 , 0 , 0
       0     .06       0   245.9    .045       0   263.5     .06       0
Bank Sta=245.9,263.5
XS Rating Curve= 0 ,0
Exp/Cntr=0.3,0.1

Type RM Length L Ch R = 1 ,15912.2 ,409.4,404.5,401.3
XS GIS Cut Line= 2
     1832453.474      625703.091     1831967.316      625932.243
#Sta/Elev= 30
       0  778.45     9.8  776.19    19.5  774.52    29.3  773.44    48.9  772.47
    78.2  771.77   107.5   771.5   117.3  771.28   146.6  770.15   156.4  769.58
   166.1  768.83   195.4  766.26   205.2  765.59     215   765.1   244.3   764.3
   264.4763.2325   273.6   762.8   282.6762.7173   283.4  762.71     342  764.06
   361.6  764.63   371.3  765.62   381.1  768.29   390.9  772.41     430  790.17
     469  808.68   488.6  817.66   498.4   822.3   508.1  827.27   537.5  843.27
#Mann= 3 , 0 , 0
       0     .06       0   264.4    .045       0   282.6     .06       0
Bank Sta=264.4,282.6
XS Rating Curve= 0 ,0
Exp/Cntr=0.3,0.1

Type RM Length L Ch R = 1 ,15508.4 ,426.8,419.1,409.7
XS GIS Cut Line= 2
     1832256.536       625374.85     1831757.822      625689.517
#Sta/Elev= 30
       0  855.41     9.8  853.42    29.5  848.27    49.1  841.59    68.8  833.41
    98.3  819.28   167.1  782.65   186.7  773.06   196.6  768.88   206.4  766.56
   235.9   763.6   268.5759.7233     285  759.08   294.3759.2792     344  761.69
   383.3   764.5     403  767.13   412.8  768.89   422.6   771.3   432.4  774.39
   442.3   778.2   452.1  782.71   461.9  787.97   471.8  793.83   481.6  800.24
   511.1  820.33   520.9  826.57   530.7  832.23   550.4  841.88   589.7   858.7
#Mann= 3 , 0 , 0
       0     .06       0   268.5    .045       0   294.3     .06       0
Bank Sta=268.5,294.3
XS Rating Curve= 0 ,0
Exp/Cntr=0.3,0.1

Type RM Length L Ch R = 1 ,15088   ,391.9,348.2,302
XS GIS Cut Line= 2
     1831975.092      624989.859     1831569.675      625502.806
#Sta/Elev= 30
       0  899.51     9.8   894.4      39  877.18    48.8  871.87    58.6   867.1
    97.6  849.93   146.4  827.85   156.1   823.1   165.9  817.84   185.4  806.37
   224.4  781.54   234.2  776.06     244   772.7   263.5  768.46   273.2  765.62
   292.8  758.87   302.5  756.85   309.9756.4839   312.3  756.36   329.5756.7686
   419.6   759.9   429.4  761.02   439.1  762.75   478.2  771.64   497.7   777.5
   517.2  784.03   546.5  793.24   575.8  803.74     605  816.32   653.8  839.81
#Mann= 3 , 0 , 0
       0     .06       0   309.9    .045       0   329.5     .06       0
Bank Sta=309.9,329.5
XS Rating Curve= 0 ,0
Exp/Cntr=0.3,0.1

Type RM Length L Ch R = 1 ,14742.5 ,64.7,106,149.8
XS GIS Cut Line= 4
      1831653.15      624764.223     1831554.462       624921.59
     1831585.411      625020.625     1831430.491      625133.588
#Sta/Elev= 30
       0  808.49    19.6     803    29.3  799.95    39.1   796.1    48.9  791.96
    58.7  788.21    68.4  785.15    78.2  782.98      88  781.26    97.8  779.91
   107.5  778.79   117.3  777.94   127.1  776.68   136.9  774.72   146.6  771.94
   156.4  768.78   166.2  765.44   185.8  758.05   198.2 757.264   204.6  756.91
     214  756.65   232.9  755.61   242.4  755.52   261.2  755.06   270.2755.1174
   289.5  755.46     347  759.93   366.2   760.8   414.1  762.34   481.2  763.06
#Mann= 3 , 0 , 0
       0     .06       0   198.2    .045       0   270.2     .06       0
Bank Sta=198.2,270.2
XS Rating Curve= 0 ,0
Exp/Cntr=0.3,0.1

Type RM Length L Ch R = 1 ,14634.1 ,322.4,339,355.6
XS GIS Cut Line= 4
     1831602.318      624732.346     1831488.953      624913.117
     1831515.316      624997.479     1831395.141      625085.107
#Sta/Elev= 30
       0  790.42    29.1  782.45    38.8  779.93    48.5  777.92    67.9  775.28
    77.6  773.85    87.3  771.82      97  769.43   116.4  764.29   135.8  759.35
   145.5  757.57   155.2  755.88     158755.4817   164.9   754.5   174.6  753.62
   183.5  753.85   184.3  753.87     194  754.96   203.7  756.13   213.4  757.03
   223.2  757.47     233  757.84   242.8   758.1   262.5  758.34   282.1  758.44
   291.9  758.57   301.8  758.81   376.1  761.85   413.3   763.1   450.5   764.2
#Mann= 3 , 0 , 0
       0     .06       0     158    .045       0   183.5     .06       0
Bank Sta=158,183.5
XS Rating Curve= 0 ,0
Exp/Cntr=0.3,0.1

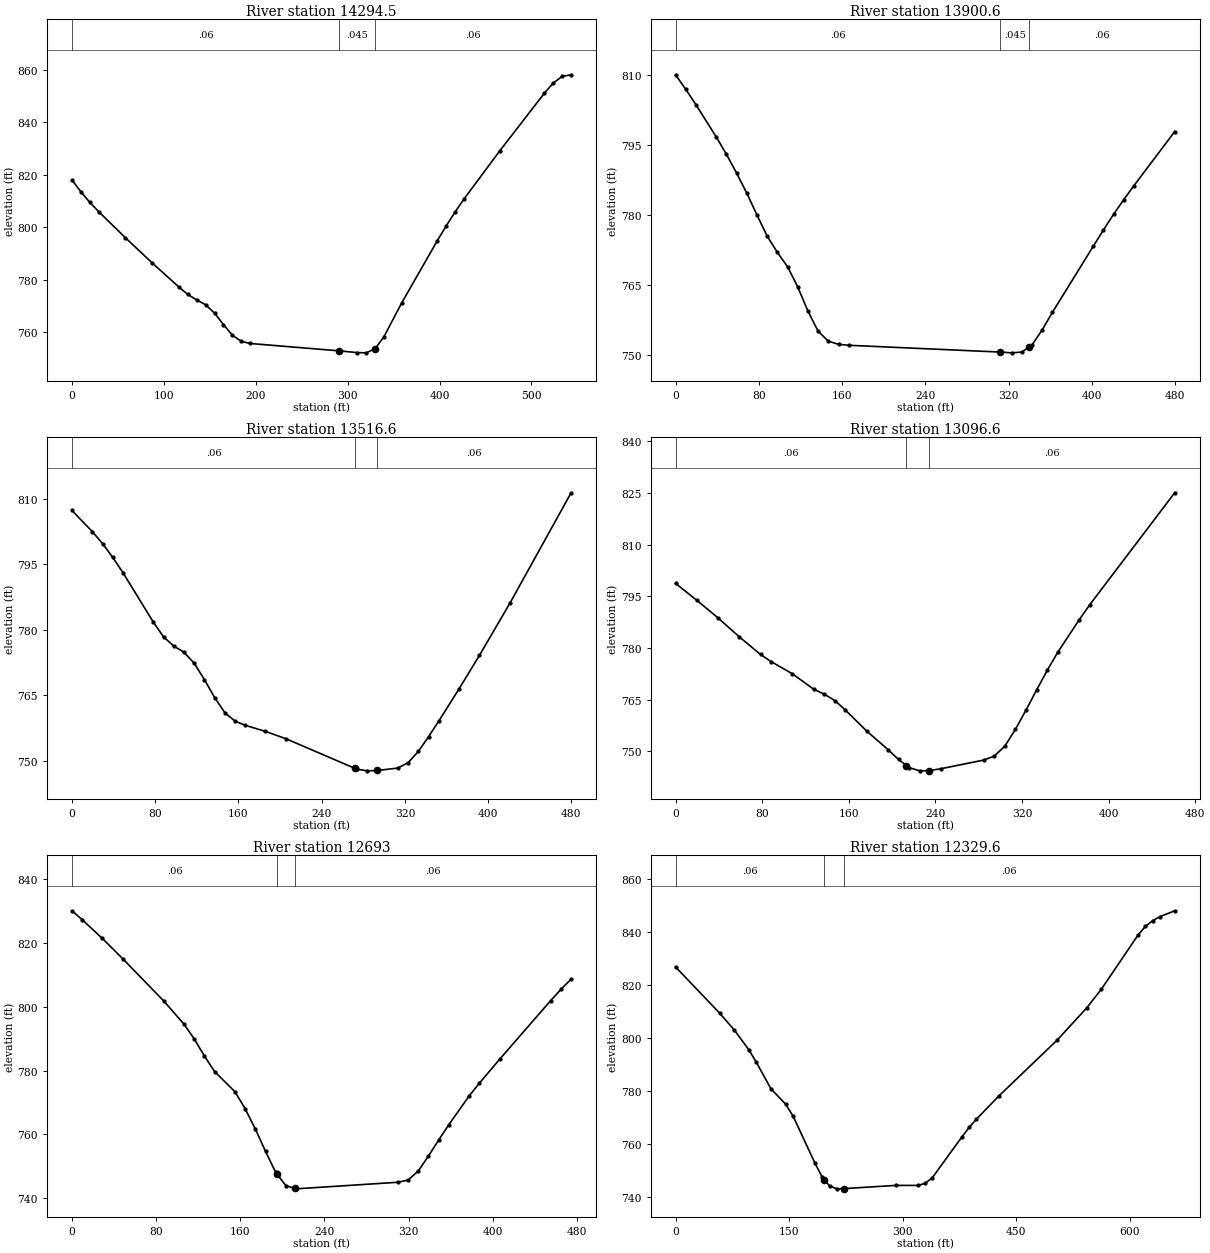
Type RM Length L Ch R = 1 ,14294.5 ,392.6,393.9,395.2
XS GIS Cut Line= 2
     1831643.314      624507.925     1831123.387      624665.335
#Sta/Elev= 30
       0  818.03     9.7  813.51    19.4  809.49    29.1  805.93    58.2  795.97
    87.3  786.38   116.4  777.18   126.1  774.34   135.8  772.29   145.5   770.4
   155.2  767.24   164.9  762.83   174.6   758.8   184.3  756.46     194  755.65
     291  752.83   310.4  752.17   320.1  752.08   329.8  753.61   339.5  758.22
   358.9  771.15   397.7  794.92   407.4  800.55   417.1  805.87   426.8  810.83
   465.6  829.13   514.1   851.1   523.8     855   533.5  857.52   543.2  858.13
#Mann= 3 , 0 , 0
       0     .06       0     291    .045       0   329.8     .06       0
Bank Sta=291,329.8
XS Rating Curve= 0 ,0
Exp/Cntr=0.3,0.1

Type RM Length L Ch R = 1 ,13900.6 ,378.2,383.7,389.2
XS GIS Cut Line= 2
     1831509.732      624165.623     1831044.464      624280.714
#Sta/Elev= 30
       0  810.06     9.8  806.95    19.6  803.66    39.1  796.74    48.9  793.02
    58.7     789    68.5  784.67    78.2  780.03      88  775.49    97.8  772.02
   107.6  768.92   117.4   764.6   127.2   759.4   136.9  755.14   146.7     753
   156.5  752.32   166.3  752.12     312 750.663   322.8   750.5   332.6  750.67
   339.8   751.8   342.4  752.21   352.1  755.44   361.9  759.18     401   773.3
   410.8   776.8   420.6  780.16   430.4  783.32   440.2  786.33   479.3  797.89
#Mann= 3 , 0 , 0
       0     .06       0     312    .045       0   339.8     .06       0
Bank Sta=312,339.8
XS Rating Curve= 0 ,0
Exp/Cntr=0.3,0.1

Type RM Length L Ch R = 1 ,13516.6 ,435.8,419.6,403.5
XS GIS Cut Line= 2
     1831481.116      623862.936     1831001.383      623865.073
#Sta/Elev= 30
       0  807.32    19.6  802.48    29.4  799.74    39.2   796.6      49   793.1
    78.3  781.74    88.1  778.37    97.9  776.29   107.7  774.87   117.5  772.36
   127.3  768.61   137.1  764.51   146.9  761.07   156.6  759.12   166.4  758.18
     186  756.76   205.6  755.09     272748.3027   274.1  748.11   283.9  747.74
   293.4 747.818   313.3  748.38   323.1  749.61   332.9  752.19   342.7  755.55
   352.5  759.11     372   766.5   391.6  774.16     421  786.15   479.7  811.37
#Mann= 3 , 0 , 0
       0     .06       0     272    .045       0   293.4     .06       0
Bank Sta=272,293.4
XS Rating Curve= 0 ,0
Exp/Cntr=0.3,0.1

Type RM Length L Ch R = 1 ,13096.6 ,409.7,403.3,396.9
XS GIS Cut Line= 2
     1831233.268      623363.893     1830879.283      623659.428
#Sta/Elev= 30
       0  798.76    19.6  793.85    39.2  788.75    58.9  783.24    78.5  778.13
    88.3  776.05   107.9  772.54   127.6  768.06   137.4  766.62   147.2  764.76
     157  761.99   176.6  755.92   196.2  750.56     206  747.68   213.3745.9221
   215.8  745.32   225.7  744.39   234.3744.4425   245.3  745.01   284.5   747.5
   294.3  748.63   304.2  751.56     314  756.44   323.8  762.02   333.6  767.88
   343.4  773.55   353.2  778.82   372.8  788.15   382.6  792.53   461.1  825.01
#Mann= 3 , 0 , 0
       0     .06       0   213.3    .045       0   234.3     .06       0
Bank Sta=213.3,234.3
XS Rating Curve= 0 ,0
Exp/Cntr=0.3,0.1

Type RM Length L Ch R = 1 ,12693   ,361.7,363.3,364.9
XS GIS Cut Line= 2
     1830937.546      623067.497     1830673.842       623461.92
#Sta/Elev= 30
       0  830.13     9.7  827.34      29  821.44    48.4  815.06    87.2  801.87
   106.5  794.59   116.2  789.97   125.9  784.61   135.6  779.73   154.9  773.41
   164.6  768.09   174.3  761.72     184  754.71   193.7  748.09   194.8747.6162
   203.3  743.97     212743.0467     213  742.94   309.8     745   319.5  745.69
   329.2  748.54   338.9  753.24   348.6  758.25   358.3  763.07   377.6  772.08
   387.3  776.08   406.7  783.62   455.1  801.98   464.8  805.46   474.5  808.71
#Mann= 3 , 0 , 0
       0     .06       0   194.8    .045       0     212     .06       0
Bank Sta=194.8,212
XS Rating Curve= 0 ,0
Exp/Cntr=0.3,0.1

Type RM Length L Ch R = 1 ,12329.6 ,276.2,251.1,229.7
XS GIS Cut Line= 2
     1830672.973      622850.086     1830268.352      623370.972
#Sta/Elev= 30
       0  826.84    58.2   809.4    77.6  803.01      97  795.47   106.7  790.84
   126.1  780.77   145.5  774.96   155.2  770.53   184.3  752.64     194  747.26
   196.5746.4238   203.7     744   213.4  742.96   222.5743.0444     291  744.26
   320.1  744.25   329.8     745   339.5  747.24   378.3  762.54     388  766.19
   397.7  769.32   426.8  777.93   504.4  799.21   543.2  811.31   562.6  818.37
   611.1  838.87   620.8  842.12   630.5  844.32   640.2  845.85   659.6  848.06
#Mann= 3 , 0 , 0
       0     .06       0   196.5    .045       0   222.5     .06       0
Bank Sta=196.5,222.5
XS Rating Curve= 0 ,0
Exp/Cntr=0.3,0.1

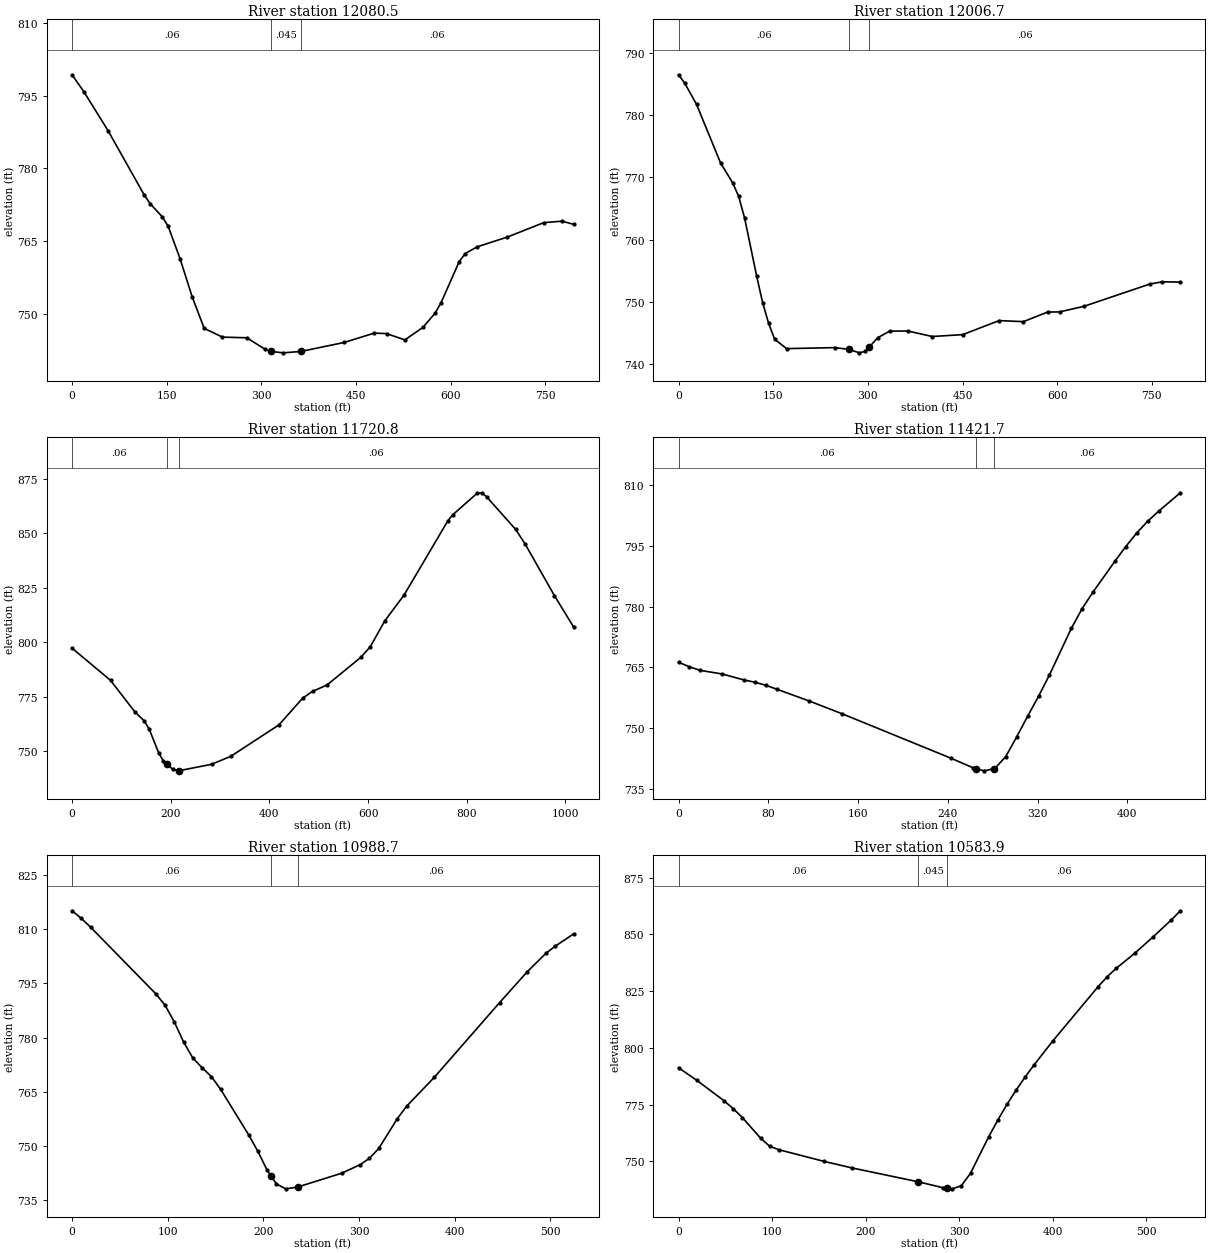
Type RM Length L Ch R = 1 ,12080.5 ,61.2,71.8,79.8
XS GIS Cut Line= 4
     1830489.536      622528.068     1830387.984       622711.07
     1830349.123      623026.679     1830158.254      623214.591
#Sta/Elev= 30
       0  799.27      19  795.72    57.1  787.74   114.2  774.55   123.7  772.72
   142.7  770.06   152.2   768.1   171.2  761.36   190.3  753.56   209.3  747.06
   238.2  745.25   276.7  745.11   305.6  742.77   315.5742.2957   334.6  742.01
   362.4 742.295   430.9  744.14   479.1  746.08   498.4  745.97   527.3  744.67
     556  747.26   575.1  750.16   584.7  752.34   613.4  760.79   622.9  762.45
   642.1  763.85   689.9  765.86   747.3  768.82     776  769.12   795.1  768.47
#Mann= 3 , 0 , 0
       0     .06       0   315.5    .045       0   362.4     .06       0
Bank Sta=315.5,362.4
XS Rating Curve= 0 ,0
Exp/Cntr=0.3,0.1

Type RM Length L Ch R = 1 ,12006.7 ,255.1,285.5,314.8
XS GIS Cut Line= 4
     1830441.384      622513.132     1830339.832      622696.134
     1830300.971      623011.743     1830110.102      623199.654
#Sta/Elev= 30
       0  786.53     9.5  785.24    28.5  781.77    66.6  772.34    85.6  769.17
    95.1  767.01   104.6   763.5   123.7  754.18   133.2  749.87   142.7  746.54
   152.2  743.97   171.2  742.45   247.8  742.61     270742.3263   286.4  741.77
     296  742.02   302.2 742.687   315.3  744.18   334.6  745.27   363.5  745.28
     402   744.4   450.2   744.7     508  746.96   546.4  746.79   584.7  748.33
   603.8  748.36   642.1  749.25   747.3  752.86   766.4   753.2   795.1  753.16
#Mann= 3 , 0 , 0
       0     .06       0     270    .045       0   302.2     .06       0
Bank Sta=270,302.2
XS Rating Curve= 0 ,0
Exp/Cntr=0.3,0.1

Type RM Length L Ch R = 1 ,11720.8 ,289.6,299,308.4
XS GIS Cut Line= 3
     1830497.612       622469.63     1829870.875      622615.177
     1829613.232      622885.657
#Sta/Elev= 30
       0  797.37      78  782.59   126.7  768.31   146.2  763.99     156  760.39
   175.5  749.38   185.2  745.52   191.5744.0993   204.7  741.74   214.5  741.09
   215.8741.1086   282.7  744.09   321.7  747.75   419.2  762.16   467.9  774.56
   487.4  777.54   516.7  780.47   584.9   793.1   604.4  798.02   633.7  809.88
   672.9  821.74   761.4  855.71   771.2  858.48   820.4  868.35   830.2  868.66
     840  866.86     899  851.86   918.7  844.99   977.6  821.46    1017  806.92
#Mann= 3 , 0 , 0
       0     .06       0   191.5    .045       0   215.8     .06       0
Bank Sta=191.5,215.8
XS Rating Curve= 0 ,0
Exp/Cntr=0.3,0.1

Type RM Length L Ch R = 1 ,11421.7 ,446.9,433,419
XS GIS Cut Line= 2
     1830481.435      622307.682     1830042.936      622219.308
#Sta/Elev= 30
       0  766.29     9.7  765.16    19.4  764.27    38.9  763.38    58.4   761.9
    68.1  761.34    77.8  760.58    87.5  759.63   116.7  756.68   145.9  753.54
   243.1  742.53   262.6  740.19   265.3739.9773   272.3  739.44   281.1739.9628
     282  740.02   291.7  742.98   301.4  747.82   311.2  752.94   320.9  757.86
   330.6  763.12   350.1  774.64   359.8  779.56   369.5  783.64     389  791.25
   398.7  794.89   408.4  798.22   418.1  801.11   427.9  803.59   447.3  808.17
#Mann= 3 , 0 , 0
       0     .06       0   265.3    .045       0   281.1     .06       0
Bank Sta=265.3,281.1
XS Rating Curve= 0 ,0
Exp/Cntr=0.3,0.1

Type RM Length L Ch R = 1 ,10988.7 ,385.8,404.7,423.5
XS GIS Cut Line= 2
     1830468.233      621789.391     1829985.583      621994.937
#Sta/Elev= 30
       0  815.11     9.7  812.99    19.4  810.56    87.4  792.16    97.2  788.97
   106.9  784.33   116.6  778.79   126.3  774.33     136  771.65   145.7  769.19
   155.4  765.64   184.6  753.09   194.3  748.49     204  743.26   208.3741.5766
   213.7  739.47   223.4  738.13   235.7738.6236   281.7  742.44   301.2  744.82
   310.9  746.59   320.6   749.3     340  757.54   349.7  760.99   378.9  769.06
   446.9  789.67     476  798.28   495.4  803.34   505.2  805.33   524.6  808.75
#Mann= 3 , 0 , 0
       0     .06       0   208.3    .045       0   235.7     .06       0
Bank Sta=208.3,235.7
XS Rating Curve= 0 ,0
Exp/Cntr=0.3,0.1

Type RM Length L Ch R = 1 ,10583.9 ,194.8,197.4,200.3
XS GIS Cut Line= 2
     1830427.263       621649.97     1829940.211      621424.422
#Sta/Elev= 30
       0  791.25    19.5  785.72    48.8  776.67    58.6  773.16    68.3  769.32
    87.8  760.19    97.6  756.63   107.4  755.12   156.1  749.94   185.4  747.12
   256.6740.9708     283  738.37   287.1738.1677   292.8  737.89   302.5  739.26
   312.3  744.78   331.8  760.89   341.6  768.25   351.3  775.13   361.1  781.42
   370.8  787.24   380.6  792.68   400.1  802.96   448.9  827.06   458.7  831.46
   468.4  835.16     488  841.72   507.5  848.91     527  856.37   536.7  860.43
#Mann= 3 , 0 , 0
       0     .06       0   256.6    .045       0   287.1     .06       0
Bank Sta=256.6,287.1
XS Rating Curve= 0 ,0
Exp/Cntr=0.3,0.1

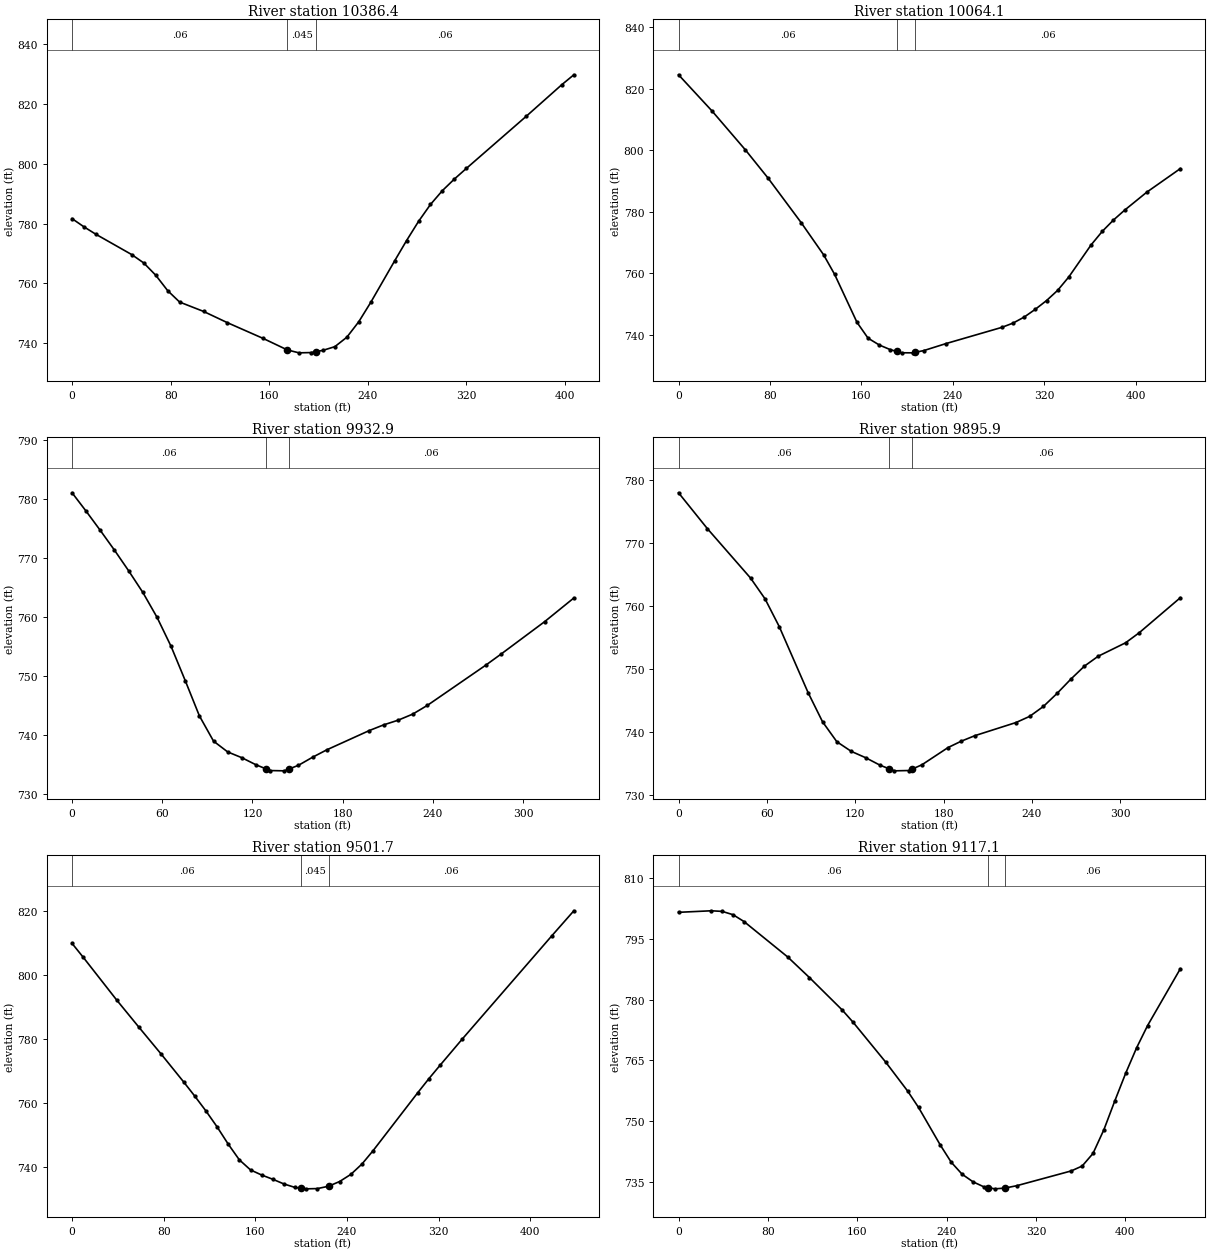
Type RM Length L Ch R = 1 ,10386.4 ,332.5,322.3,311.7
XS GIS Cut Line= 2
     1830451.793      621479.303     1830108.213      621260.605
#Sta/Elev= 30
       0  781.64     9.7  778.88    19.4  776.39    48.5  769.58    58.2  766.79
    67.9  762.69    77.6  757.52    87.3  753.69   106.7  750.56   126.1  746.78
   155.2  741.49   174.8  737.64   184.2  736.68   193.9  736.77   197.8737.0676
   203.6  737.51   213.3  738.75     223   741.9   232.7  747.09   242.4  753.56
   261.8  767.47   271.5  774.29   281.2   780.7   290.9  786.38   300.6  791.03
   310.3   794.9     320  798.45   368.5  815.88   397.6  826.55   407.3  829.84
#Mann= 3 , 0 , 0
       0     .06       0   174.8    .045       0   197.8     .06       0
Bank Sta=174.8,197.8
XS Rating Curve= 0 ,0
Exp/Cntr=0.3,0.1

Type RM Length L Ch R = 1 ,10064.1 ,132,131.1,132.5
XS GIS Cut Line= 2
     1830632.048      621135.444     1830195.218      621089.867
#Sta/Elev= 30
       0  824.51    29.3  812.75    58.6  800.06    78.1  791.05   107.4  776.42
   126.9  766.04   136.6  759.65   156.2  744.04   165.9  738.89   175.7  736.68
   185.4  735.16     191  734.58   195.2  734.15     205  734.13   207.3734.3087
   214.7  734.87   234.2  737.15     283  742.41   292.8   743.8   302.6  745.77
   312.3  748.29   322.1  751.12   331.8  754.43   341.6   758.8   361.1  769.21
   370.9  773.62   380.6  777.27   390.4  780.49   409.9  786.37   439.2  794.01
#Mann= 3 , 0 , 0
       0     .06       0     191    .045       0   207.3     .06       0
Bank Sta=191,207.3
XS Rating Curve= 0 ,0
Exp/Cntr=0.3,0.1

Type RM Length L Ch R = 1 ,9932.9  ,41.3,37.2,36.7
XS GIS Cut Line= 4
      1830571.95      620989.778     1830440.273      620984.899
     1830365.898      620972.517     1830239.498      620979.551
#Sta/Elev= 30
       0   781.1     9.4  777.96    18.8  774.71    28.2  771.37    37.6  767.88
    47.1  764.19    56.5  759.99    65.9  755.03    75.3  749.23    84.7  743.26
    94.1  738.98   103.5  737.15   112.9  736.17   122.4  734.96     129734.2803
   131.8  733.99   141.2  733.94   144.2  734.24   150.6  734.88     160  736.25
   169.5  737.51   197.7  740.77   207.2  741.73   216.9  742.53   226.6  743.56
   236.4  745.05   275.3  751.88   285.1  753.69   314.3  759.23   333.8  763.26
#Mann= 3 , 0 , 0
       0     .06       0     129    .045       0   144.2     .06       0
Bank Sta=129,144.2
XS Rating Curve= 0 ,0
Exp/Cntr=0.3,0.1

Type RM Length L Ch R = 1 ,9895.9  ,390.5,394,391.7
XS GIS Cut Line= 4
     1830585.974      620929.365     1830430.626      620947.704
     1830396.104      620939.074     1830247.408      620933.119
#Sta/Elev= 29
       0  777.99    19.6   772.3    48.9  764.47    58.7  761.19    68.4  756.77
      88   746.3    97.8  741.68   107.5  738.52   117.3  736.99   127.1  735.98
   136.9  734.79   143.1734.2192   146.6   733.9   156.4  733.95   158.3734.1403
   165.3  734.86   183.1   737.6     192   738.6   201.3  739.48   229.2  741.56
   238.5  742.54   247.8  744.11   257.1  746.18   266.4  748.43   275.7  750.51
     285  752.07   303.6   754.2   312.9   755.8   340.8  761.35
#Mann= 3 , 0 , 0
       0     .06       0   143.1    .045       0   158.3     .06       0
Bank Sta=143.1,158.3
XS Rating Curve= 0 ,0
Exp/Cntr=0.3,0.1

Type RM Length L Ch R = 1 ,9501.7  ,380.4,384.5,388.7
XS GIS Cut Line= 2
     1830626.614      620561.291     1830188.592      620553.915
#Sta/Elev= 30
       0  809.98     9.7  805.67    38.9  792.32    58.4  783.79    77.9  775.36
    97.4  766.72   107.1  762.29   116.8  757.68   126.6  752.68   136.3   747.3
     146  742.39   155.8  739.22   165.5  737.63   175.2  736.31     185  734.83
   194.7  733.74   199.8733.5139   204.4  733.31   214.2  733.39   223.9  734.12
   233.6   735.6   243.4  737.83   253.1  741.06   262.8  745.23   301.8  763.34
   311.5  767.71   321.3  771.92   340.7  780.12   418.6  812.26   438.1  820.18
#Mann= 3 , 0 , 0
       0     .06       0   199.8    .045       0   223.9     .06       0
Bank Sta=199.8,223.9
XS Rating Curve= 0 ,0
Exp/Cntr=0.3,0.1

Type RM Length L Ch R = 1 ,9117.1  ,349.9,349.9,349.9
XS GIS Cut Line= 2
     1830758.007      620258.812     1830319.751      620159.901
#Sta/Elev= 30
       0  801.55    29.3  801.93    39.1  801.78    48.8  800.96    58.6  799.28
    97.7  790.54   117.2  785.45   146.5  777.46   156.3  774.42   185.6  764.54
   205.1  757.45   214.9  753.39   234.4   744.1   244.2  739.86   253.9  736.91
   263.7  735.03   273.5  733.78   277.4733.5898   283.2   733.3   291.9733.4758
   302.8  734.07   351.6  737.72   361.4  738.93   371.1  742.03   380.9  747.92
   390.7  755.05   400.4  761.85   410.2  768.14     420  773.61   449.3  787.62
#Mann= 3 , 0 , 0
       0     .06       0   277.4    .045       0   291.9     .06       0
Bank Sta=277.4,291.9
XS Rating Curve= 0 ,0
Exp/Cntr=0.3,0.1

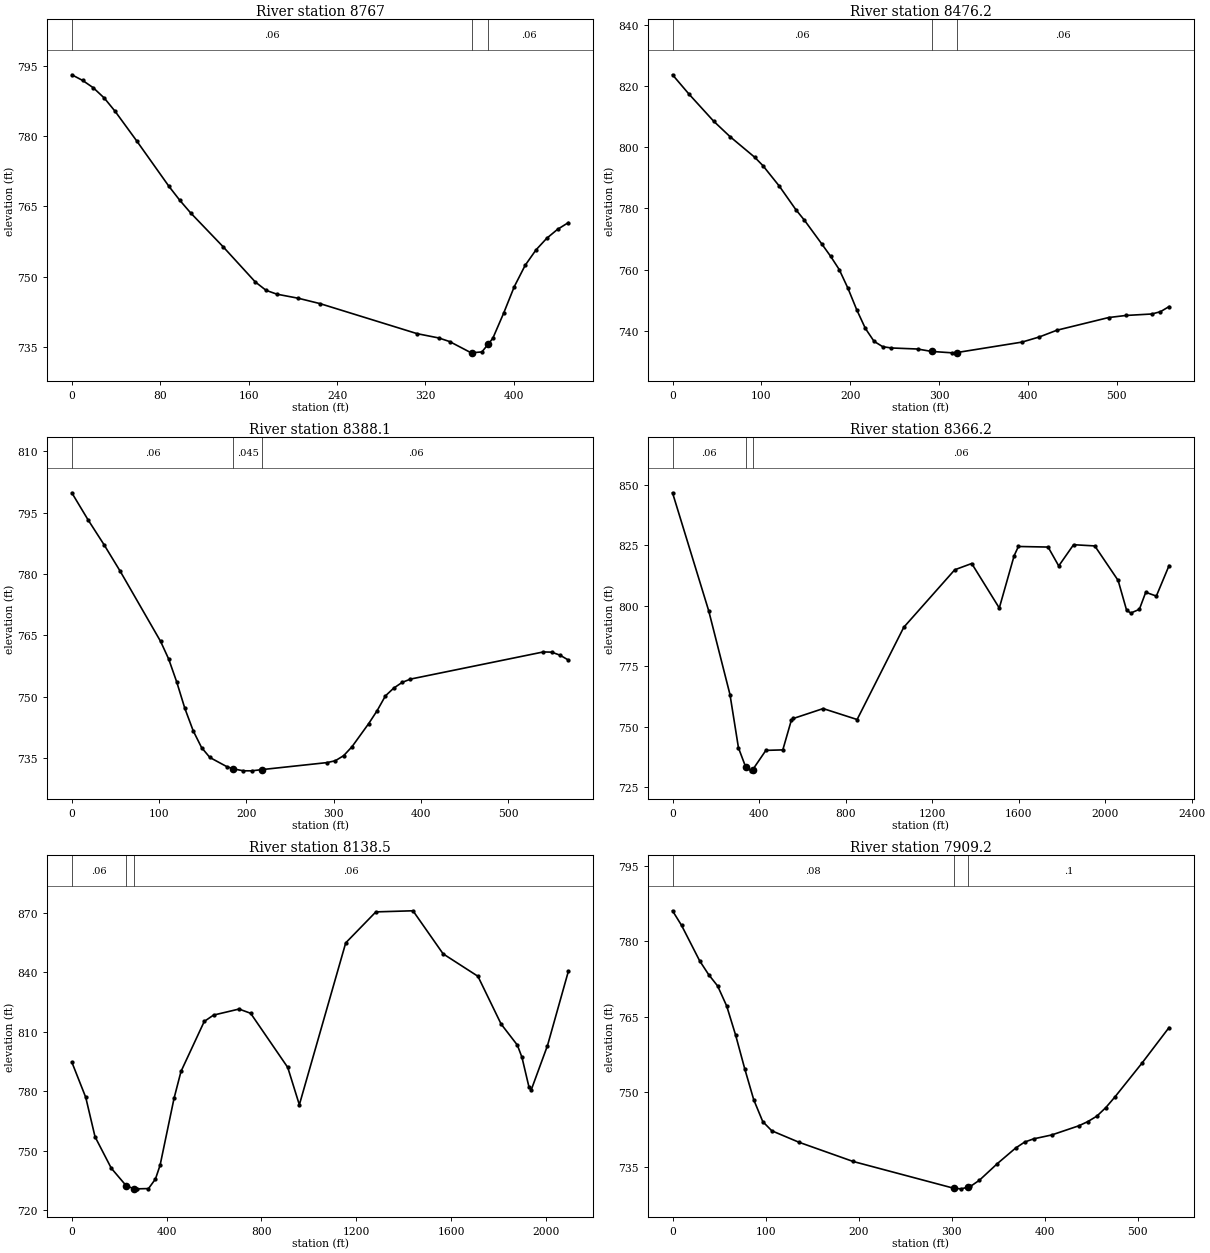
Type RM Length L Ch R = 1 ,8767    ,315.3,290.9,266.5
XS GIS Cut Line= 2
     1830834.693      619940.345     1830396.437      619841.433
#Sta/Elev= 30
       0  793.17     9.8  791.96    19.5  790.38    29.3  788.21    39.1  785.38
    58.6  779.06    87.9   769.3    97.7  766.32   107.4  763.65   136.7  756.43
     166  748.85   175.8  747.05   185.6  746.23   205.1  745.35   224.6  744.21
   312.5  737.78   332.1  736.86   341.8   736.1   361.4  733.68   361.9733.6884
   371.1  733.88     377  735.62   380.9  736.77   390.7  742.14   400.4  747.86
   410.2   752.4     420   755.7   429.7  758.18   439.5   760.1   449.3  761.54
#Mann= 3 , 0 , 0
       0     .06       0   361.9    .045       0     377     .06       0
Bank Sta=361.9,377
XS Rating Curve= 0 ,0
Exp/Cntr=0.3,0.1

Type RM Length L Ch R = 1 ,8476.2  ,89.4,89.2,88.9
XS GIS Cut Line= 5
     1830801.406      619458.287     1830663.215      619470.571
     1830499.336       619594.45     1830461.493      619674.342
     1830435.538       619797.89
#Sta/Elev= 30
       0  823.66    18.5  817.36    46.2  808.53    64.7  803.46    92.5  796.72
   101.7  793.99   120.2  787.28   138.7  779.64   148.5  776.13   168.1  768.35
   177.9  764.38   187.6  760.04   197.4  753.94   207.2  746.97     217  740.82
   226.8  736.59   236.6  734.83   246.3  734.42   275.7  734.08   291.6733.2888
   314.8  732.83   320.2732.9343   393.3  736.34   412.9  738.03   432.6  740.22
   490.8  744.36   510.3  745.04   539.4  745.52   549.1  746.27   558.8  747.94
#Mann= 3 , 0 , 0
       0     .06       0   291.6    .045       0   320.2     .06       0
Bank Sta=291.6,320.2
XS Rating Curve= 0 ,0
Exp/Cntr=0.3,0.1

Type RM Length L Ch R = 1 ,8388.1  ,17.1,21.3,38.1
XS GIS Cut Line= 4
     1830723.882       619427.78     1830594.645      619434.668
     1830419.445      619583.238     1830379.075      619788.747
#Sta/Elev= 30
       0  799.85    18.5  793.28      37  787.14    55.5  780.66   101.7  763.54
   110.9  759.26   120.2   753.6   129.4  747.22     139  741.72   148.6  737.62
   158.1   735.2   177.3  732.99   184.8732.4295   196.4  731.95     206  731.94
   218.3 732.256   292.1  733.95   301.7   734.4   311.3  735.65   320.8  737.82
     340  743.49   349.6  746.63   359.1  750.24   368.6  752.14   378.2  753.53
   387.7  754.34     540  760.98   549.5  760.93     559  760.19   568.6     759
#Mann= 3 , 0 , 0
       0     .06       0   184.8    .045       0   218.3     .06       0
Bank Sta=184.8,218.3
XS Rating Curve= 0 ,0
Exp/Cntr=0.3,0.1

Type RM Length L Ch R = 1 ,8366.2  ,204.1,227,237.4
XS GIS Cut Line= 5
     1830885.525      619397.393     1830591.772      619426.206
     1830535.512      619463.952      1830408.98      619478.011
     1829115.789       620736.99
#Sta/Elev= 30
       0  846.62   167.3  797.89   265.6  763.32   304.8  741.33   338.5733.3303
   362.9  731.83   370.9  732.34   431.5  740.28   509.8  740.48   549.1   752.7
   558.9  753.46   696.2  757.53   853.2  753.02  1068.9   791.1  1304.4  814.83
  1382.8  817.42  1510.3  799.04    1579  820.66  1598.6  824.45  1735.9  824.21
    1785  816.42  1853.6  825.18  1951.7  824.68  2059.6  810.42  2098.9  798.07
  2118.5  796.98  2157.7  798.51  2187.1  805.53  2236.2  803.98    2295  816.58
#Mann= 3 , 0 , 0
       0     .06       0   338.5    .045       0   370.9     .06       0
Bank Sta=338.5,370.9
XS Rating Curve= 0 ,0
Exp/Cntr=0.3,0.1

Type RM Length L Ch R = 1 ,8138.5  ,226.6,229.3,232
XS GIS Cut Line= 3
     1830743.527       619304.66     1830204.517      619156.867
     1828891.041      619954.073
#Sta/Elev= 30
       0  794.71    58.8  776.87      98  756.96   166.7  741.06   229.5732.2367
   262.5730.6845   274.6  730.66   323.6  730.79     353  735.63   372.6  742.62
   431.4  776.37   460.8  789.97   558.9  815.22     598  818.42   705.7  821.48
   754.6  819.34   911.2  791.99   960.2  773.12  1155.9  854.91  1283.1  870.56
  1439.7  871.12  1566.9  849.36  1713.7  838.04  1811.6   813.9  1880.1  803.28
  1899.6  797.08    1929  782.18  1938.8  780.67  2007.3  803.02  2095.4  840.55
#Mann= 3 , 0 , 0
       0     .06       0   229.5    .045       0   262.5     .06       0
Bank Sta=229.5,262.5
XS Rating Curve= 0 ,0
Exp/Cntr=0.3,0.1

Type RM Length L Ch R = 1 ,7909.2  ,426.9,413,399
XS GIS Cut Line= 2
     1830828.883      619150.761     1830347.252      618921.126
#Sta/Elev= 30
       0  786.13     9.7  783.22    29.1  776.16    38.8  773.39    48.5  771.11
    58.2  767.12    67.9  761.25    77.6  754.58    87.3  748.38      97  744.02
   106.7  742.19   135.8  739.91     194  736.07   302.6730.6981   310.4   730.6
     318730.9752   320.1  731.08   329.8  732.32   349.2  735.66   368.6  738.73
   378.4  739.94     388  740.58   407.5  741.36   436.6  743.19   446.3  744.03
     456  745.12   465.7  746.84   475.4  748.95   504.5  755.71   533.6  762.82
#Mann= 3 , 0 , 0
       0     .08       0   302.6    .045       0     318      .1       0
Bank Sta=302.6,318
XS Rating Curve= 0 ,0
Exp/Cntr=0.3,0.1