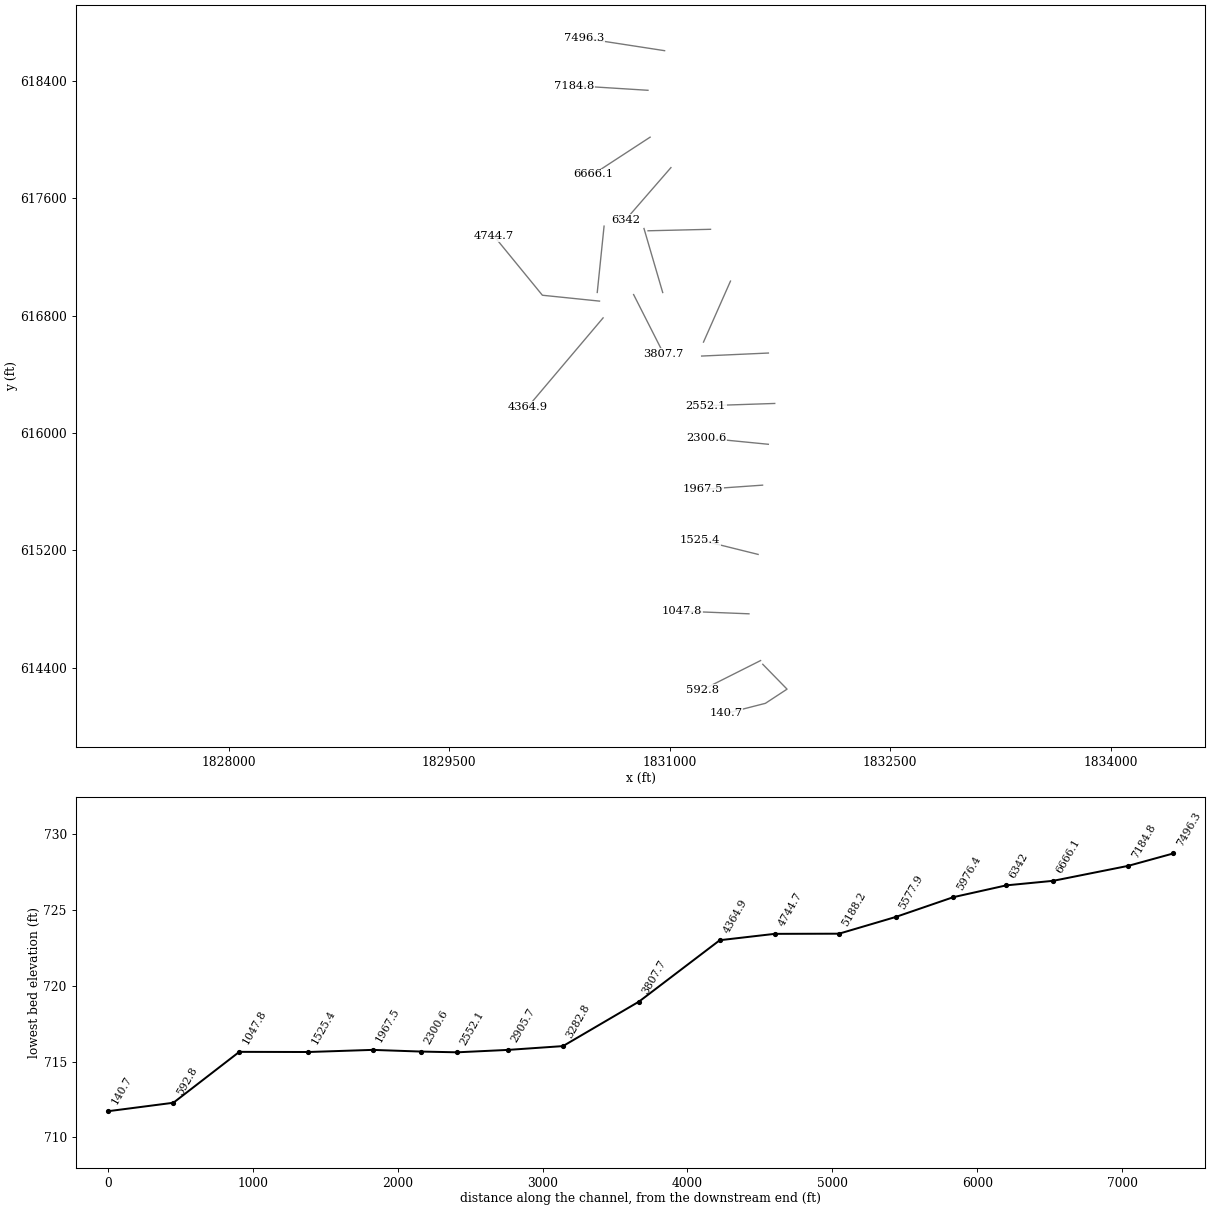
HEC-RAS study CoxFork.prj: CoxFork

--- CoxFork.g01 (geometry) --- (continued)

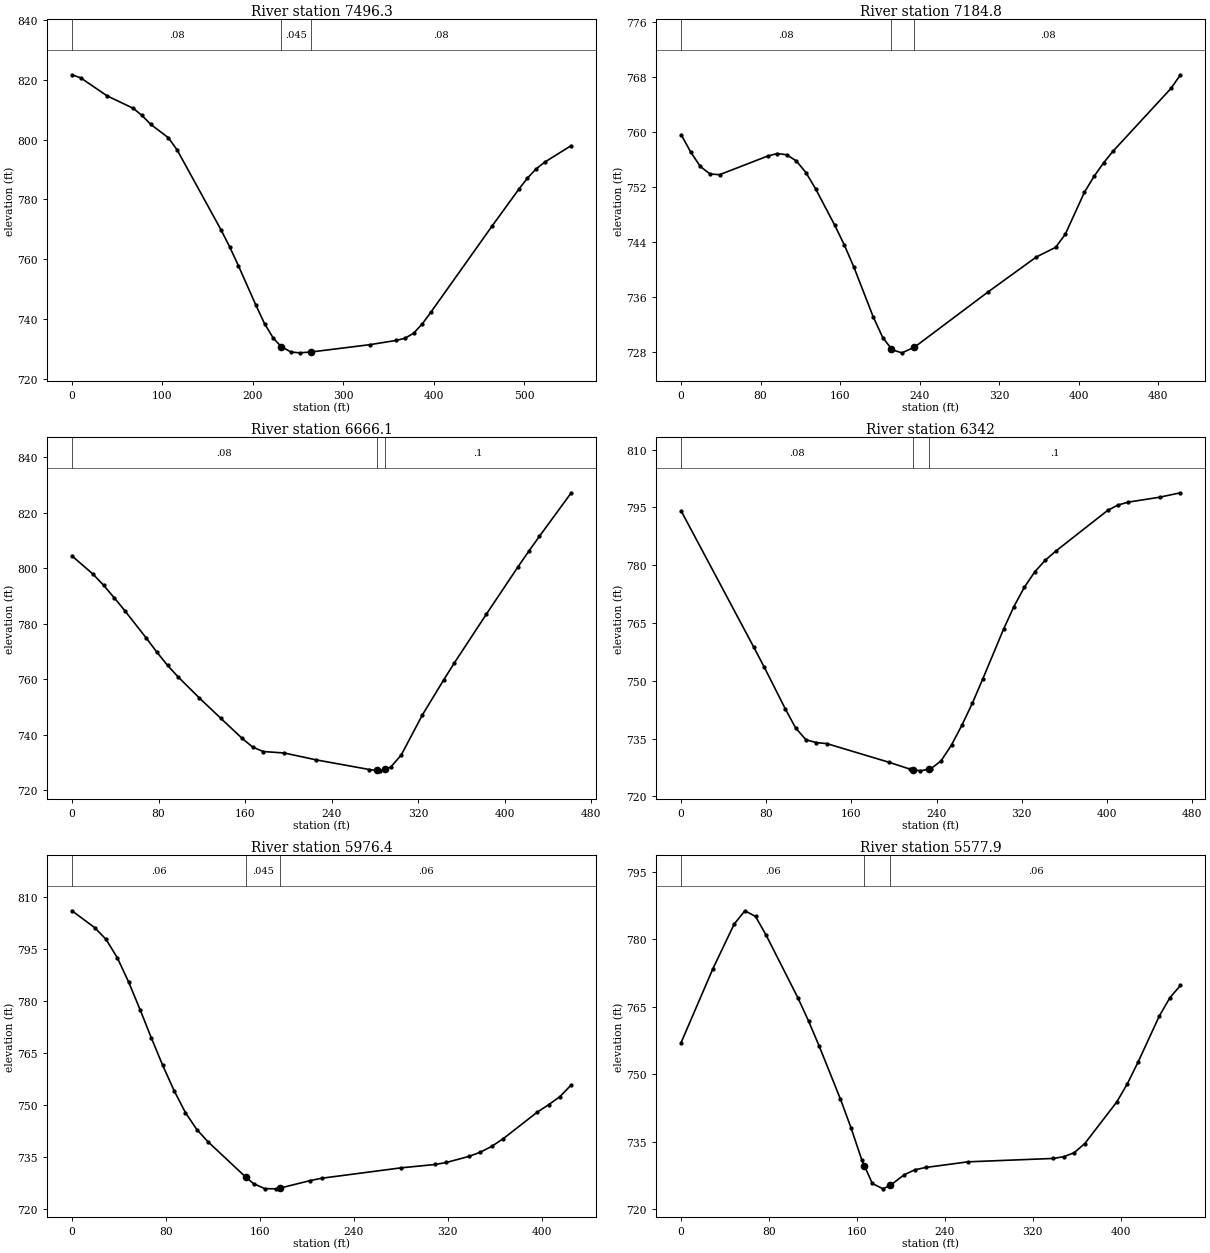
Type RM Length L Ch R = 1 ,7496.3  ,309,311.5,313.9
XS GIS Cut Line= 2
     1830965.273      618605.218     1830420.014      618689.366
#Sta/Elev= 30
       0  821.64     9.7  820.61    38.7  814.62    67.8  810.43    77.4  808.04
    87.1  805.06   106.5  800.62   116.2  796.54   164.6   769.9   174.2   764.2
   183.9  757.87   203.3  744.63   212.9  738.44   222.6   733.6   231.1 730.866
     242  729.02   251.7  728.75   264.6729.0489   329.1  731.48   358.1  732.89
   367.8   733.6   377.5   735.3   387.2  738.47   396.8  742.42   464.6  771.28
   493.6  783.35   503.3  787.13     513  790.24   522.7  792.52   551.7  797.99
#Mann= 3 , 0 , 0
       0     .08       0   231.1    .045       0   264.6     .08       0
Bank Sta=231.1,264.6
XS Rating Curve= 0 ,0
Exp/Cntr=0.3,0.1

Type RM Length L Ch R = 1 ,7184.8  ,504.1,518.6,533.2
XS GIS Cut Line= 2
     1830852.216      618335.237     1830350.675      618366.774
#Sta/Elev= 30
       0   759.6     9.7  757.05    19.3  754.98      29  753.89    38.7  753.78
      87  756.48    96.6  756.85   106.3  756.67     116  755.77   125.6  754.09
   135.3  751.74   154.6  746.45   164.3  743.56     174  740.32   193.3  733.16
     203  730.12   211.5728.5508   212.6  728.35   222.3  727.93   234.8 728.749
   309.2   736.8   357.6  741.85   376.9  743.24   386.6  745.14   405.9  751.24
   415.6  753.55   425.2  755.51   434.9  757.23   492.9  766.29   502.5  768.28
#Mann= 3 , 0 , 0
       0     .08       0   211.5    .045       0   234.8     .08       0
Bank Sta=211.5,234.8
XS Rating Curve= 0 ,0
Exp/Cntr=0.3,0.1

Type RM Length L Ch R = 1 ,6666.1  ,317.8,324,330.3
XS GIS Cut Line= 2
     1830866.796      618015.765     1830480.587      617763.357
#Sta/Elev= 30
       0  804.38    19.6  797.76    29.4  793.73    39.3  789.18    49.1  784.52
    68.7  774.76    78.5  769.69    88.4  764.91    98.2  760.74   117.8  753.16
   137.4  745.92   157.1   738.7   166.9  735.52   176.7   733.9   196.3  733.36
   225.8  730.88   274.9  727.41   281.7727.0797   284.7  726.94   289.2727.5415
   294.5  728.25   304.3  732.67   323.9  747.13   343.6  759.75   353.4  765.84
   382.8   783.3   412.3   800.5   422.1  806.03   431.9  811.39   461.4  827.11
#Mann= 3 , 0 , 0
       0     .08       0   281.7    .045       0   289.2      .1       0
Bank Sta=281.7,289.2
XS Rating Curve= 0 ,0
Exp/Cntr=0.3,0.1

Type RM Length L Ch R = 1 ,6342    ,384.4,365.5,346.5
XS GIS Cut Line= 2
     1831008.372       617808.29     1830701.202      617453.937
#Sta/Elev= 30
       0  794.09    68.4  758.64    78.2  753.48    97.7   742.8   107.5  737.79
   117.2  734.71     127  733.96   136.8  733.71   195.4  728.85   214.9  727.09
   217.4  726.98   224.7  726.64   232.9727.0762   234.5  727.16   244.2  729.24
     254  733.37   263.8  738.52   273.6  744.22   283.3  750.46   302.9  763.42
   312.6  769.27   322.4  774.27   332.2  778.29     342  781.27   351.7   783.6
   400.6   794.2   410.3   795.6   420.1  796.36   449.4  797.63     469  798.78
#Mann= 3 , 0 , 0
       0     .08       0   217.4    .045       0   232.9      .1       0
Bank Sta=217.4,232.9
XS Rating Curve= 0 ,0
Exp/Cntr=0.3,0.1

Type RM Length L Ch R = 1 ,5976.4  ,428.4,398.5,368.6
XS GIS Cut Line= 2
      1831277.67      617387.816     1830852.667       617377.71
#Sta/Elev= 30
       0   806.1    19.3  801.25      29  797.87    38.6  792.56    48.3  785.51
      58  777.58    67.6   769.4    77.3  761.47      87  754.18    96.6  747.87
   106.3  742.98   115.9  739.42   147.8729.3019   154.6  727.36   164.2  725.92
   173.9  725.86   177.4726.0981   202.9  728.25   212.6  728.92   280.2  731.92
   309.2  732.89   318.8  733.47   338.2  735.24   347.8  736.45   357.5  738.15
   367.2  740.34   396.1  747.98   405.8  750.13   415.5  752.49   425.1  755.87
#Mann= 3 , 0 , 0
       0     .06       0   147.8    .045       0   177.4     .06       0
Bank Sta=147.8,177.4
XS Rating Curve= 0 ,0
Exp/Cntr=0.3,0.1

Type RM Length L Ch R = 1 ,5577.9  ,398.3,389.9,381.4
XS GIS Cut Line= 2
     1830952.421      616956.916     1830825.096      617393.143
#Sta/Elev= 30
       0  757.04      29  773.48    48.3  783.36      58  786.31    67.7  785.05
    77.4  780.88   106.4  766.91     116   761.8   125.7  756.22     145  744.47
   154.7  738.05   164.4  730.98   166.8729.6664     174  725.74   183.7  724.55
   190.5725.3422     203  727.67   212.7  728.78   222.4  729.29   261.1  730.55
   338.4   731.3   348.1  731.68   357.7  732.58   367.4  734.62   396.4  743.83
   406.1  747.89   415.8  752.68   435.1   762.9   444.8     767   454.4  769.74
#Mann= 3 , 0 , 0
       0     .06       0   166.8    .045       0   190.5     .06       0
Bank Sta=166.8,190.5
XS Rating Curve= 0 ,0
Exp/Cntr=0.3,0.1

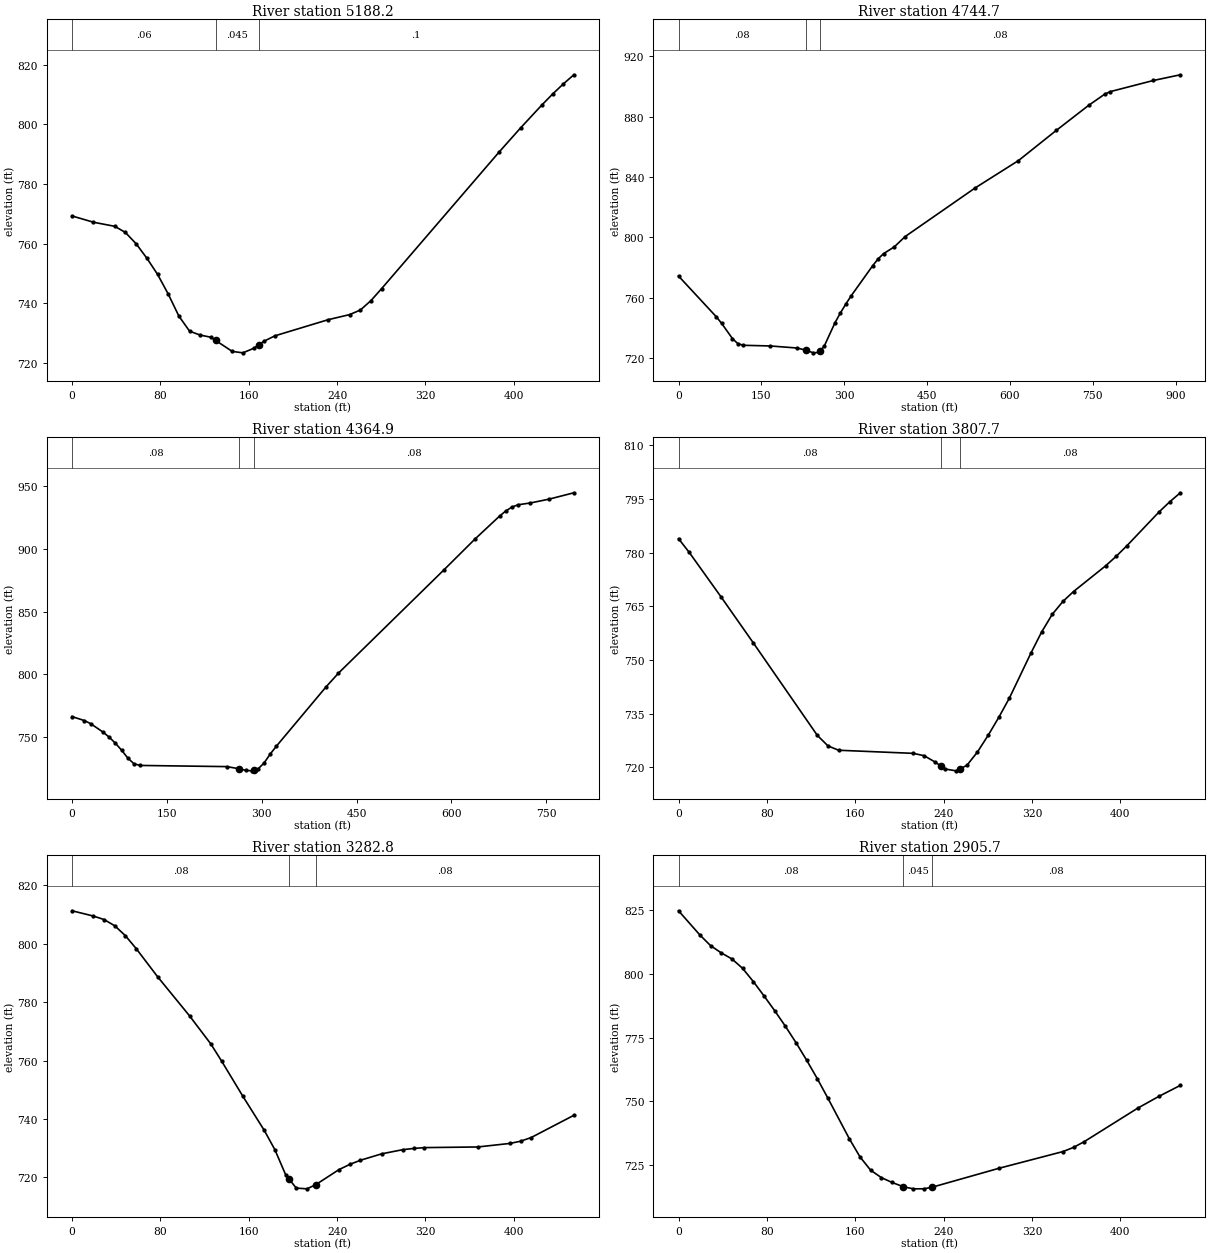
Type RM Length L Ch R = 1 ,5188.2  ,407.7,443.2,478.7
XS GIS Cut Line= 2
     1830507.206       616957.38     1830553.612      617409.433
#Sta/Elev= 30
       0  769.29    19.3   767.2    38.7  765.82    48.3  763.77      58  759.99
    67.7  755.16    77.4  749.75      87   743.2    96.7  735.77   106.4  730.71
     116   729.4   125.7  728.68   130.1727.5868     145  723.93   154.7  723.45
   164.4  724.96     169726.1196     174  727.38   183.7  729.15     232  734.56
   251.4  736.26   261.1   737.8   270.7  740.96   280.4  744.99   386.8  790.74
   406.1  798.76   425.4  806.45   435.1   810.1   444.8   813.5   454.4  816.58
#Mann= 3 , 0 , 0
       0     .06       0   130.1    .045       0     169      .1       0
Bank Sta=130.1,169
XS Rating Curve= 0 ,0
Exp/Cntr=0.3,0.1

Type RM Length L Ch R = 1 ,4744.7  ,358.3,379.8,401.5
XS GIS Cut Line= 3
     1830522.647      616898.366     1830134.114      616938.358
     1829806.873      617339.556
#Sta/Elev= 30
       0  774.31    68.4  747.31    78.1  742.92    97.6  732.87   107.4   729.5
   117.2  728.44     166     728   214.8  726.63     230725.2462   244.1  723.44
   253.9  723.74   255.5724.4067   263.6  727.78   283.2  743.37   292.9   749.8
   302.7  755.71   312.5  761.22   351.5  781.19   361.3   785.7   371.1  789.14
   390.6  793.65   410.1  800.45   537.1  832.72   615.3   850.8   683.6  870.74
   742.2  887.35   771.6  894.84   781.3  896.47   859.5  903.86   908.3  907.64
#Mann= 3 , 0 , 0
       0     .08       0     230    .045       0   255.5     .08       0
Bank Sta=230,255.5
XS Rating Curve= 0 ,0
Exp/Cntr=0.3,0.1

Type RM Length L Ch R = 1 ,4364.9  ,529.9,556.9,583.6
XS GIS Cut Line= 2
     1830546.992      616784.016     1830035.194      616177.504
#Sta/Elev= 30
       0   766.3    19.6  763.12    29.4  760.66      49  753.93    58.8  749.84
    68.6  745.04    78.4  739.46    88.2   733.2      98  728.62   107.8  727.33
   244.9  726.39   264.2724.6649   274.3  723.44   284.1  723.02     288723.5771
   293.9  724.42   303.7  729.33   313.5   736.5   323.3   742.8   401.7  790.03
   421.3  800.98   587.8  883.24   636.8  907.79     676  926.26   685.8  930.36
   695.6  933.48   705.4  935.35     725   936.8   754.4  939.84   793.6  944.92
#Mann= 3 , 0 , 0
       0     .08       0   264.2    .045       0     288     .08       0
Bank Sta=264.2,288
XS Rating Curve= 0 ,0
Exp/Cntr=0.3,0.1

Type RM Length L Ch R = 1 ,3807.7  ,545.5,525,504.4
XS GIS Cut Line= 2
     1830754.479       616942.87     1830959.851      616537.496
#Sta/Elev= 30
       0  783.91     9.7  780.07    38.7  767.54    67.7  754.77   125.7  728.88
   135.4  725.93     145  724.73   212.7  723.86   222.4   723.2     232  721.49
   238.1  720.21   241.7  719.46   251.4  718.97   254.5719.4605   261.1   720.5
   270.7  724.25   280.4  728.92   290.1  733.98   299.7  739.38   319.1   751.9
   328.7  757.75   338.4  762.74   348.1  766.36   357.7  769.13   386.8  776.33
   396.4     779   406.1  781.96   435.1  791.38   444.8  794.22   454.4  796.75
#Mann= 3 , 0 , 0
       0     .08       0   238.1    .045       0   254.5     .08       0
Bank Sta=238.1,254.5
XS Rating Curve= 0 ,0
Exp/Cntr=0.3,0.1

Type RM Length L Ch R = 1 ,3282.8  ,402,377.1,352.4
XS GIS Cut Line= 2
       1831413.4      617034.752     1831229.821      616619.055
#Sta/Elev= 30
       0  811.32    19.3  809.51      29  808.31    38.7  806.17    48.3  802.77
      58  798.39    77.4  788.74   106.4   775.3   125.7  765.66   135.4  759.82
   154.7  747.73     174   736.1   183.7  729.41   193.4  720.87   196.6719.3419
     203  716.29   212.7  716.03   220.6717.4388   241.7  722.62   251.4  724.39
   261.1  725.82   280.4  728.03   299.7  729.47   309.4  729.87   319.1  730.16
   367.4  730.38   396.4  731.59   406.1  732.34   415.8  733.62   454.4  741.23
#Mann= 3 , 0 , 0
       0     .08       0   196.6    .045       0   220.6     .08       0
Bank Sta=196.6,220.6
XS Rating Curve= 0 ,0
Exp/Cntr=0.3,0.1

Type RM Length L Ch R = 1 ,2905.7  ,353.2,353,352.7
XS GIS Cut Line= 2
     1831671.156      616544.488     1831217.192      616523.919
#Sta/Elev= 30
       0  824.64    19.3  815.18      29     811    38.7  808.15    48.3   805.8
      58  802.11    67.7  796.94    77.4  791.32      87  785.57    96.7  779.47
   106.4  772.99     116  766.16   125.7  758.87   135.4  751.15   154.7  735.36
   164.4  728.24     174  723.06   183.7  720.17   193.4  718.27   203.7716.5887
   212.7  715.78   222.4   715.8   229.4716.3906   290.1  723.82   348.1  730.37
   357.7     732   367.4  734.26   415.8  747.36   435.1  752.01   454.4  756.28
#Mann= 3 , 0 , 0
       0     .08       0   203.7    .045       0   229.4     .08       0
Bank Sta=203.7,229.4
XS Rating Curve= 0 ,0
Exp/Cntr=0.3,0.1

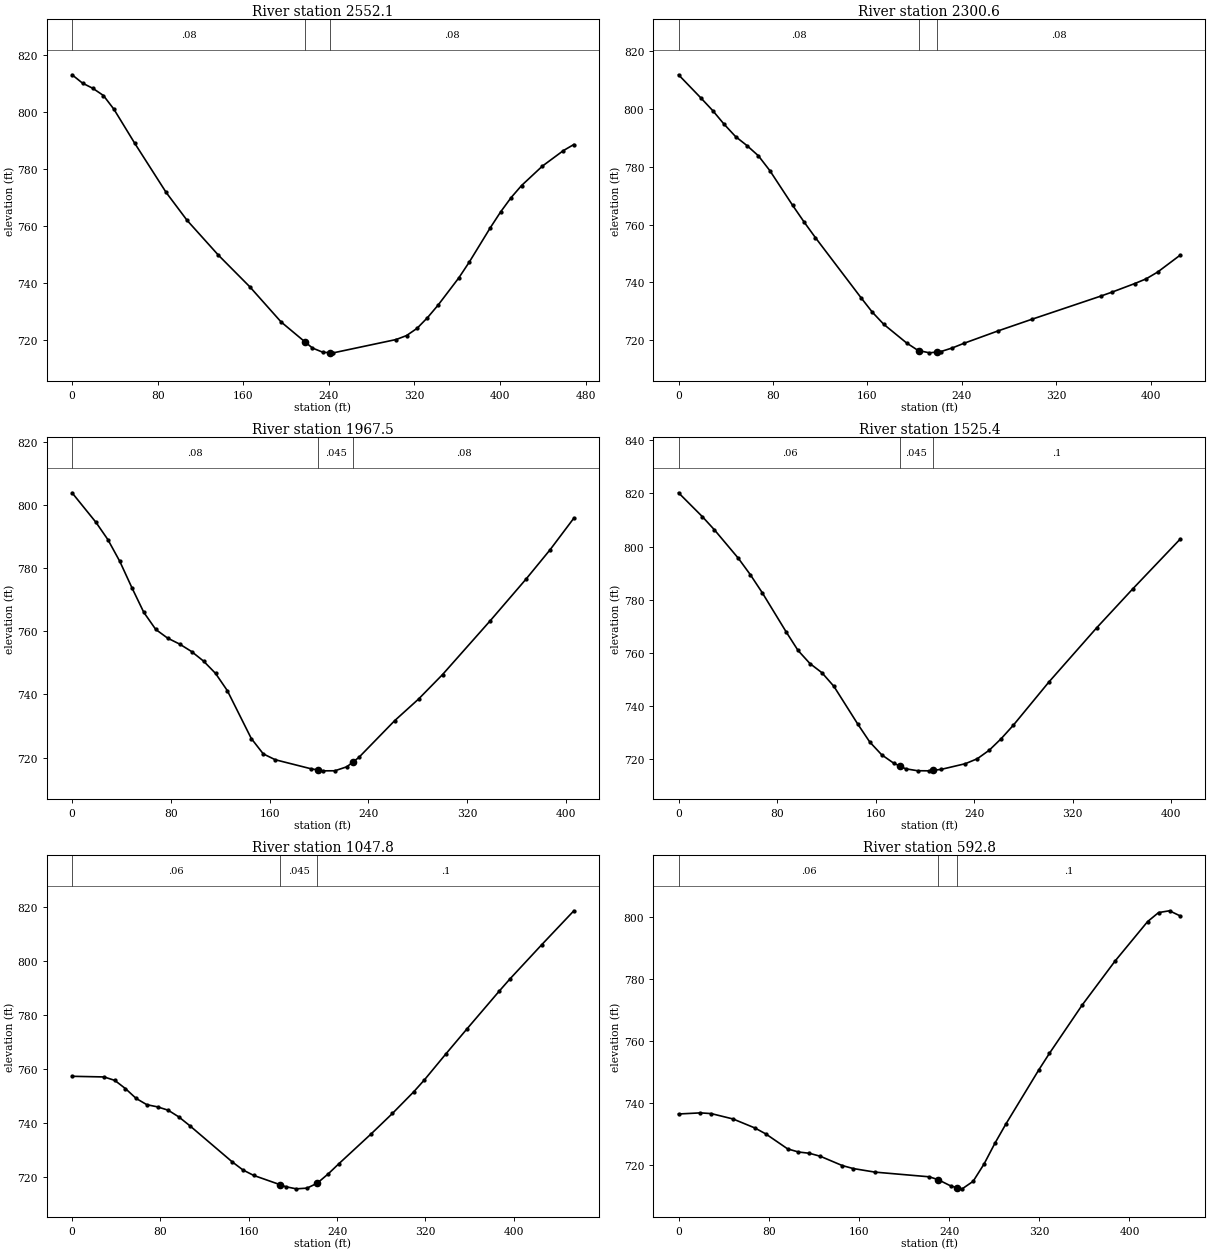
Type RM Length L Ch R = 1 ,2552.1  ,254.5,251.5,248.5
XS GIS Cut Line= 2
     1831714.349       616200.84     1831245.652      616185.262
#Sta/Elev= 30
       0  813.13     9.8  810.19    19.5  808.36    29.3  805.86    39.1  801.06
    58.6  789.09    87.9  771.89   107.5  762.08   136.8  749.86   166.1  738.79
   195.4  726.44   217.5719.5188   224.7   717.3   234.5  715.81     241715.6827
   244.2  715.62   302.9  720.29   312.6  721.67   322.4   724.2   332.2  727.96
     342  732.31   361.5  741.93   371.3  747.48   390.8  759.43   400.6  765.07
   410.3  770.04   420.1  774.29   439.6  781.11   459.2  786.54     469  788.68
#Mann= 3 , 0 , 0
       0     .08       0   217.5    .045       0     241     .08       0
Bank Sta=217.5,241
XS Rating Curve= 0 ,0
Exp/Cntr=0.3,0.1

Type RM Length L Ch R = 1 ,2300.6  ,329.3,332.9,336.5
XS GIS Cut Line= 2
     1831670.779      615922.607     1831247.709       615964.34
#Sta/Elev= 30
       0  811.82    19.3  803.65      29  799.42    38.6  794.73    48.3  790.46
      58  787.33    67.6  783.83    77.3  778.71    96.6  766.71   106.3  760.95
   115.9  755.54   154.6  734.73   164.2  729.72   173.9  725.52   193.2  719.09
   202.9   716.5   203.4 716.457   212.6  715.67   218.8 715.954   222.2  716.11
   231.9  717.36   241.6  718.94   270.5  723.23   299.5   727.3   357.5  735.26
   367.2  736.66   386.5  739.63   396.1  741.25   405.8  743.58   425.1  749.49
#Mann= 3 , 0 , 0
       0     .08       0   203.4    .045       0   218.8     .08       0
Bank Sta=203.4,218.8
XS Rating Curve= 0 ,0
Exp/Cntr=0.3,0.1

Type RM Length L Ch R = 1 ,1967.5  ,449.5,441.9,434.4
XS GIS Cut Line= 2
     1831631.589       615644.01     1831226.058       615615.55
#Sta/Elev= 30
       0  803.92    19.4  794.53      29  789.08    38.7  782.15    48.4  773.89
    58.1  766.02    67.8   760.6    77.4  757.85    87.1  755.97    96.8   753.6
   106.5  750.57   116.2  746.68   125.8  741.19   145.2  726.02   154.9  721.15
   164.6   719.3   193.6  716.43     199716.0682   203.3  715.78   212.9   715.8
   222.6  717.07   227.9718.6819   232.3  720.02   261.3  731.67   280.7  738.54
   300.1  746.29   338.8  763.38   367.8  776.58   387.2  785.84   406.5  795.88
#Mann= 3 , 0 , 0
       0     .08       0     199    .045       0   227.9     .08       0
Bank Sta=199,227.9
XS Rating Curve= 0 ,0
Exp/Cntr=0.3,0.1

Type RM Length L Ch R = 1 ,1525.4  ,472.8,477.4,482.1
XS GIS Cut Line= 2
     1831601.365      615172.004     1831206.064      615270.291
#Sta/Elev= 30
       0  820.26    19.4  811.25    29.1  806.34    48.5  795.64    58.2   789.5
    67.9   782.7    87.3  767.97      97  760.94   106.7  755.99   116.4  752.56
   126.1  747.44   145.5  733.22   155.2   726.5   164.9  721.68   174.6  718.54
     180717.3598   184.3  716.42     194  715.68   203.6  715.64   206.2715.7913
   213.4  716.21   232.8  718.33   242.5  720.19   252.2   723.4   261.9  727.75
   271.6  732.72   300.6  749.05   339.4  769.46   368.5  784.01   407.3  802.89
#Mann= 3 , 0 , 0
       0     .06       0     180    .045       0   206.2      .1       0
Bank Sta=180,206.2
XS Rating Curve= 0 ,0
Exp/Cntr=0.3,0.1

Type RM Length L Ch R = 1 ,1047.8  ,443.5,454.9,466.3
XS GIS Cut Line= 2
     1831539.164      614767.132     1831085.093      614785.175
#Sta/Elev= 30
       0  757.39      29  757.15    38.7  755.87    48.3  752.84      58  749.19
    67.7  746.86    77.4  746.05      87  744.82    96.7  742.32   106.4  739.14
     145  725.66   154.7  722.66   164.4  720.64   188.5717.1724   193.4  716.45
     203  715.65   212.7  715.91   221.9 717.712     232  721.21   241.7     725
   270.7  735.98   290.1  743.61   309.4  751.64   319.1  756.08   338.4  765.64
   357.7  775.02   386.8  788.97   396.4  793.45   425.4  806.24   454.4  818.78
#Mann= 3 , 0 , 0
       0     .06       0   188.5    .045       0   221.9      .1       0
Bank Sta=188.5,221.9
XS Rating Curve= 0 ,0
Exp/Cntr=0.3,0.1

Type RM Length L Ch R = 1 ,592.8   ,409.2,452.1,494.9
XS GIS Cut Line= 2
     1831618.035       614448.48     1831220.527      614248.144
#Sta/Elev= 30
       0  736.41    19.4  736.77      29  736.54    48.4   734.8    67.7  731.91
    77.4  729.99    96.8  725.16   106.4  724.16   116.1  723.75   125.8  722.78
   145.2   719.8   154.8  718.84   174.2  717.68   222.6  716.16   230.5715.2062
   241.9  713.14   246.8 712.712   251.6  712.29   261.3  714.71     271  720.29
   280.6  726.96   290.3  733.14   319.3  750.47     329  755.96     358   771.5
   387.1  785.65   416.1  798.43   425.8  801.32   435.5   801.9   445.1  800.22
#Mann= 3 , 0 , 0
       0     .06       0   230.5    .045       0   246.8      .1       0
Bank Sta=230.5,246.8
XS Rating Curve= 0 ,0
Exp/Cntr=0.3,0.1

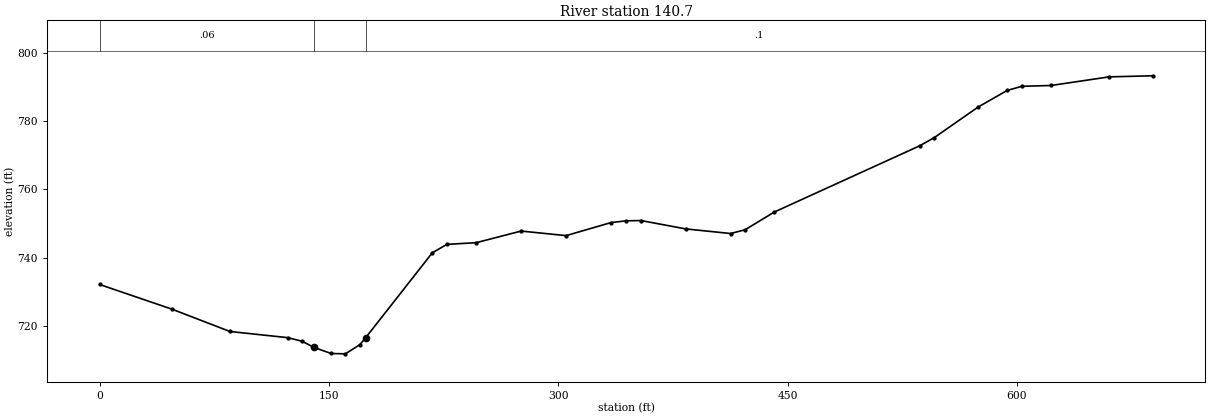
Type RM Length L Ch R = 1 ,140.7   ,137.4,140.7,144
XS GIS Cut Line= 4
     1831633.003      614423.025     1831798.117      614253.633
     1831650.857      614156.966     1831383.327      614088.523
#Sta/Elev= 30
       0  732.08    47.3  724.84    85.2  718.29     123  716.48   132.5  715.41
   140.1713.6313   151.4  711.83   160.8  711.73   170.3  714.47     174716.4602
   217.6  741.39   227.1  743.85   246.3  744.35   275.7  747.76   305.1  746.42
   334.4  750.24   344.2  750.76     354  750.85   383.4  748.39   412.7  747.04
   422.2  748.15   441.3  753.35   536.5  772.81     546  775.21   574.6  784.16
   593.6  789.03   603.2  790.24   622.2  790.48   660.3  793.01   688.8  793.33
#Mann= 3 , 0 , 0
       0     .06       0   140.1    .045       0     174      .1       0
Bank Sta=140.1,174
XS Rating Curve= 0 ,0
Exp/Cntr=0.3,0.1

Chan Stop Cuts=-1
Use User Specified Reach Order=0
Composite Channel Slope=5